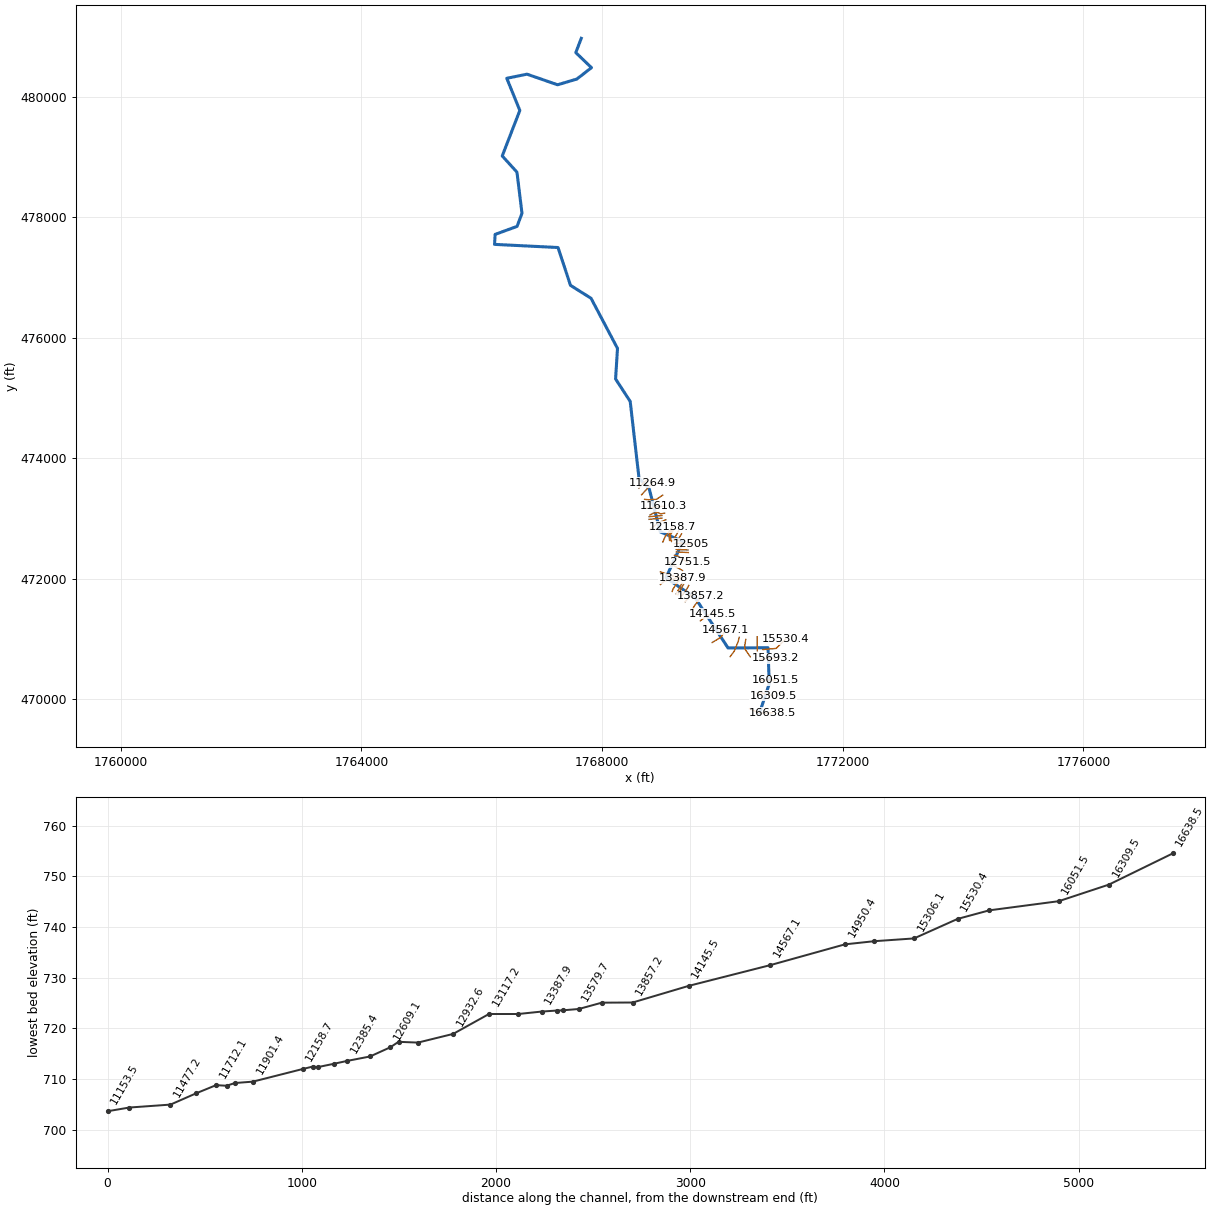
--- MIDFORK1.prj (project) ---

Proj Title=MIDFORK1
Current Plan=p01
Default Exp/Contr=0,0
English Units
Geom File=g01
Flow File=f01
Plan File=p01
BEGIN DESCRIPTION:
END DESCRIPTION:
DSS Export Rating Curves= 0
DSS Export Rating Curve Sorted= 0
DSS Export Volume Flow Curves= 0
DXF OffsetX= 0
DXF OffsetY= 0
DXF ScaleX= 0
DXF ScaleY= 0

--- MIDFORK1.p01 (plan) ---

Plan Title=Floodplain
Program Version=4.00
Geom File=g01
Flow File=f01
K Sum by GR=0
Std Step Tol=0.01
Critical Tol=0.01
Num of Std Step Trials=20
Max Error Tol=0.3
Flow Tol Ratio=0.001
Split Flow NTrial=30
Split Flow Tol=0.02
Split Flow Ratio=0.02
Log Output Level=0
Friction Slope Method=1
Unsteady Friction Slope Method=2
Unsteady Bridges Friction Slope Method=1
Global Log Level=0
CheckData=False
Run HTab=0
Run UNet=0
Run PostProcess=0
UNET Theta=0
UNET Theta Warmup=0
UNET ZTol=0
UNET ZSATol=0
UNET MxIter=0
UNET MaxInSteps=0
UNET DtIC=0
UNET DtMin=0
UNET MaxCRTS=0
UNET WFStab=0
UNET SFStab=0
UNET WFX=0
UNET SFX=0
UNET DSS MLevel=0
UNET DZMax Abort=0
UNET Convert EG Bridges=0
UNET Use Existing IB Tables=0
UNET Froude Limit=0
UNET Froude Power=0
Write IC File=0
Echo Input=False
Echo Output=False
Write Detailed=0

--- MIDFORK1.f01 (steady flow) ---

Flow Title=NFF Regression Equation
Program Version=4.10
Number of Profiles= 1
Profile Names=P100yr
River Rch & RM=MIDFORK1,Main            ,16638.5
1232.563
River Rch & RM=MIDFORK1,Main            ,11610.3
1435.928
River Rch & RM=MIDFORK1,Main            ,5883.4
1735.079
River Rch & RM=MIDFORK1,Main            ,5280.5
1966.046
River Rch & RM=MIDFORK1,Main            ,2800.1
 2032.14
Boundary for River Rch & Prof#=MIDFORK1,Main            , 1
Up Type= 0
Dn Type= 1
Dn Known WS=629.8
DSS Import GetInterval= 0
DSS Import GetPeak= 0
DSS Import FillOption= 0

--- MIDFORK1.g01 (geometry) ---

Geom Title=USGS 10m DEM
Program Version=4.10

River Reach=MIDFORK1        ,Main
Reach XY= 30
     1770614.491      469763.839     1770777.252       470252.12
     1770757.721      470853.683     1770093.658      470849.776
     1769549.387      471679.204     1769061.106      472016.443
     1769342.356      472619.308     1768966.705      472777.901
     1768782.894      473494.988      1768613.84      473666.212
     1768467.112      474943.892     1768224.083      475317.253
     1768256.201      475824.198     1767816.035      476657.046
     1767474.951      476871.073     1767267.486      477499.545
     1766212.799      477551.628     1766222.347      477717.427
     1766586.931      477850.239     1766668.528      478068.989
     1766585.194      478750.413     1766340.403      479020.378
     1766632.938      479775.587     1766415.924      480309.441
     1766751.861      480378.017     1767259.674      480201.802
     1767580.854      480297.288     1767823.379      480485.896
     1767562.963      480736.547     1767654.108      480973.092

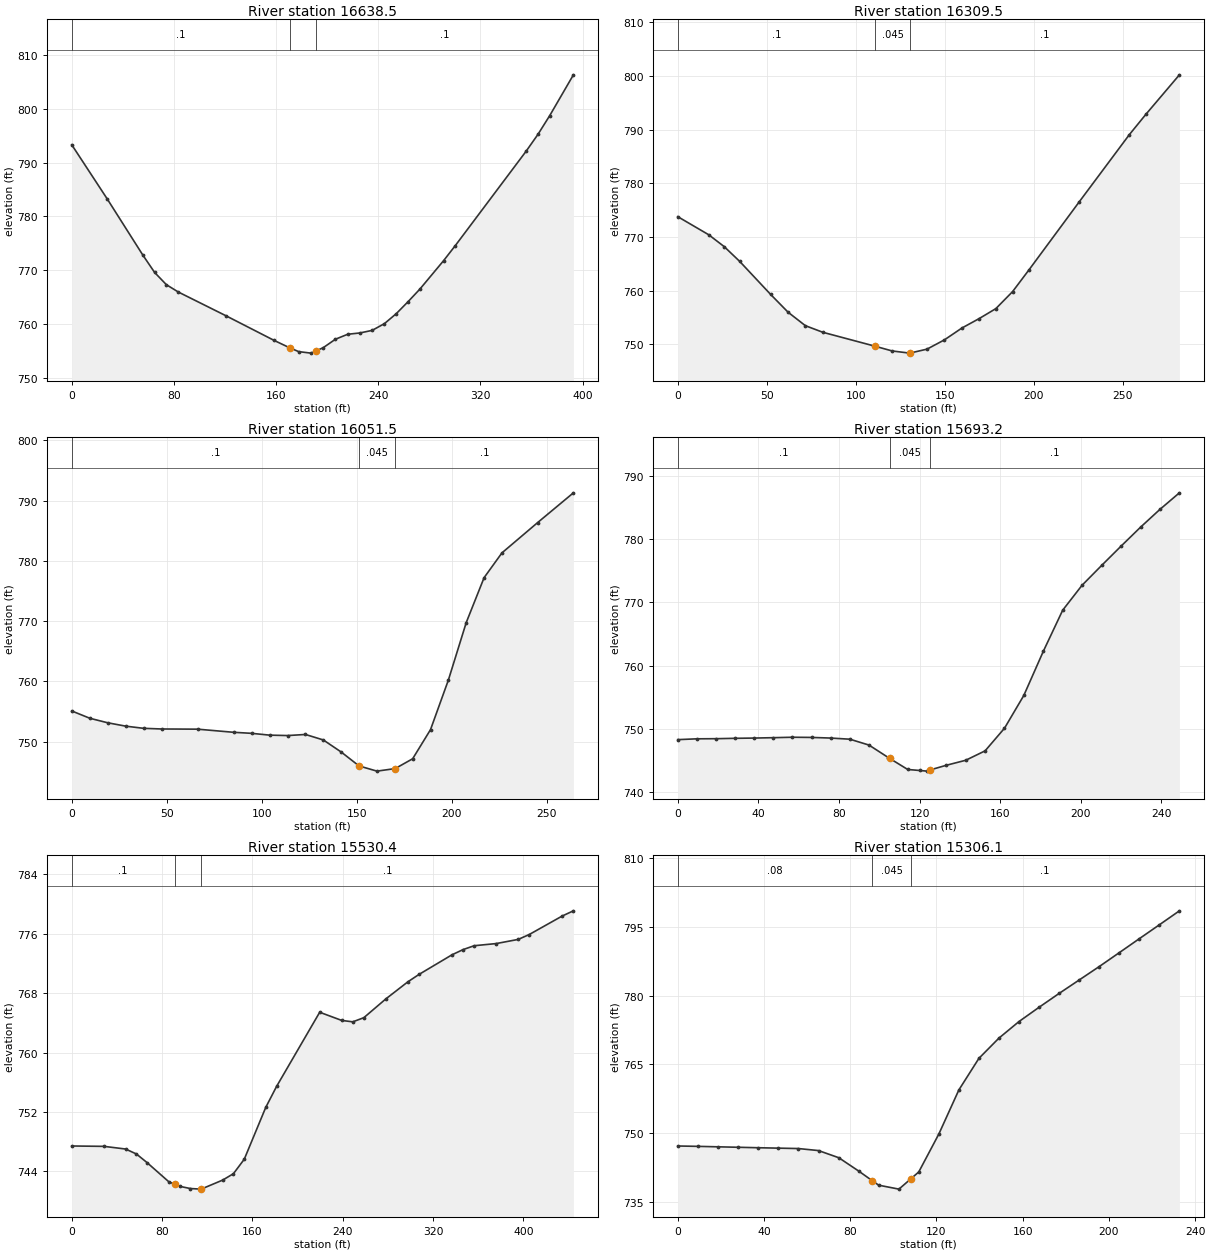
Type RM Length L Ch R = 1 ,16638.5 ,330.4,329,327.7
XS GIS Cut Line= 4
     1770451.222      469840.858     1770569.278      469787.039
     1770682.125       469764.47     1770829.694      469774.886
#Sta/Elev= 27
       0   793.3    27.8  783.22    55.6  772.81    64.9  769.55    74.1  767.28
    83.4  765.92   120.5  761.53   158.5  756.91   171.1  755.49   177.7  754.83
   187.3  754.55  191.32  754.97   196.9  755.56   206.5  757.14   216.1  758.06
   225.6   758.3   235.2  758.78   244.8  760.03   254.1  761.89   263.3  764.11
   272.6  766.46   291.1  771.73   300.3  774.54   355.8  792.11     365  795.22
   374.3  798.74   392.8  806.31
#Mann= 3 , 0 , 0
       0      .1       0   171.1    .045       0  191.32      .1       0
Bank Sta=171.1,191.32
XS Rating Curve= 0 ,0
Exp/Cntr=0.3,0.1

Type RM Length L Ch R = 1 ,16309.5 ,253.2,258,262.6
XS GIS Cut Line= 4
     1770571.014      470099.539     1770621.361      470113.428
     1770734.208      470082.178     1770843.583      470056.136
#Sta/Elev= 22
       0   773.8    17.4  770.43    26.1  768.22    34.8  765.47    52.2  759.31
      62     756    71.7   753.5    81.5  752.27   110.9  749.67   120.5  748.79
   130.3  748.39     140  749.13   149.8  750.86   159.6  753.06   169.3  754.82
   178.7  756.68   188.1  759.85   197.4  763.94   225.5  776.55   253.6  789.04
     263  792.87   281.8  800.21
#Mann= 3 , 0 , 0
       0      .1       0   110.9    .045       0   130.3      .1       0
Bank Sta=110.9,130.3
XS Rating Curve= 0 ,0
Exp/Cntr=0.3,0.1

Type RM Length L Ch R = 1 ,16051.5 ,354.1,358.3,362.3
XS GIS Cut Line= 3
     1770616.153      470307.872      1770737.68       470326.97
     1770878.305      470316.553
#Sta/Elev= 25
       0   755.1     9.5  753.89    18.9  753.14    28.4  752.58    37.8  752.22
    47.3  752.11    66.2  752.08    85.2  751.56    94.6  751.39   104.1  751.09
   113.6  751.02     123   751.2   132.4  750.29   141.8  748.29   151.2  745.98
   160.6  745.12   170.2  745.54   179.4  747.17   188.8     752   198.2  760.22
   207.6  769.76     217  777.21   226.4  781.32   245.2  786.35     264  791.28
#Mann= 3 , 0 , 0
       0      .1       0   151.2    .045       0   170.2      .1       0
Bank Sta=151.2,170.2
XS Rating Curve= 0 ,0
Exp/Cntr=0.3,0.1

Type RM Length L Ch R = 1 ,15693.2 ,164,162.8,162.4
XS GIS Cut Line= 4
     1770628.305      470663.775     1770713.375       470670.72
     1770789.764      470677.664     1770876.569        470679.4
#Sta/Elev= 30
       0  748.29     9.5  748.42      19  748.44    28.4   748.5    37.9  748.54
    47.4   748.6    56.9  748.67    66.4  748.64    75.9  748.54    85.4  748.36
    94.9  747.43   104.5  745.45   105.1  745.33   114.1  743.57   120.1  743.41
   123.7  743.31  125.33  743.51   133.3  744.24   142.9  745.03   152.5  746.52
   162.1  750.09   171.7  755.28   181.4  762.28     191  768.77   200.6  772.71
   210.3  775.84   219.9  778.88   229.6  781.89   239.2   784.7   248.9  787.33
#Mann= 3 , 0 , 0
       0      .1       0   105.1    .045       0  125.33      .1       0
Bank Sta=105.1,125.33
XS Rating Curve= 0 ,0
Exp/Cntr=0.3,0.1

Type RM Length L Ch R = 1 ,15530.4 ,189.1,224.3,258.5
XS GIS Cut Line= 3
     1770673.444      470823.497     1770892.194      470842.595
     1771053.653      470998.845
#Sta/Elev= 30
       0  747.43    28.6  747.38    47.7  747.02    57.3  746.35    66.8  745.18
    85.9  742.62    91.1  742.28    95.5     742     105   741.7   114.6  741.62
   133.7  742.84   143.2   743.7   152.8  745.65   171.8  752.62   181.4  755.45
   219.6  765.44   239.1  764.34   248.9  764.15   258.7  764.71   278.2  767.24
   297.7  769.54   307.5  770.53   336.8  773.18   346.6  773.88   356.4   774.4
   375.9  774.69   395.4  775.25   405.2  775.91   434.5  778.41   444.3   779.1
#Mann= 3 , 0 , 0
       0      .1       0    91.1    .045       0   114.6      .1       0
Bank Sta=91.1,114.6
XS Rating Curve= 0 ,0
Exp/Cntr=0.3,0.1

Type RM Length L Ch R = 1 ,15306.1 ,205,205.3,203.7
XS GIS Cut Line= 3
     1770579.694        470804.4     1770577.958      470879.053
     1770576.222      471037.039
#Sta/Elev= 28
       0  747.18     9.3   747.1    18.7     747      28   746.9    37.3   746.8
    46.7  746.71      56  746.62    65.3  746.18    74.7  744.62      84  741.69
   90.12  739.64    93.2  738.63   102.6  737.77   108.2  740.05   111.8  741.52
   121.1  749.78   130.4  759.41   139.7   766.3     149  770.72   158.3  774.33
   167.6  777.44   176.9  780.46   186.2  783.39   195.5  786.32   204.8  789.35
   214.1   792.4   223.4  795.43   232.7  798.48
#Mann= 3 , 0 , 0
       0     .08       0   90.12    .045       0   108.2      .1       0
Bank Sta=90.12,108.2
XS Rating Curve= 0 ,0
Exp/Cntr=0.3,0.1

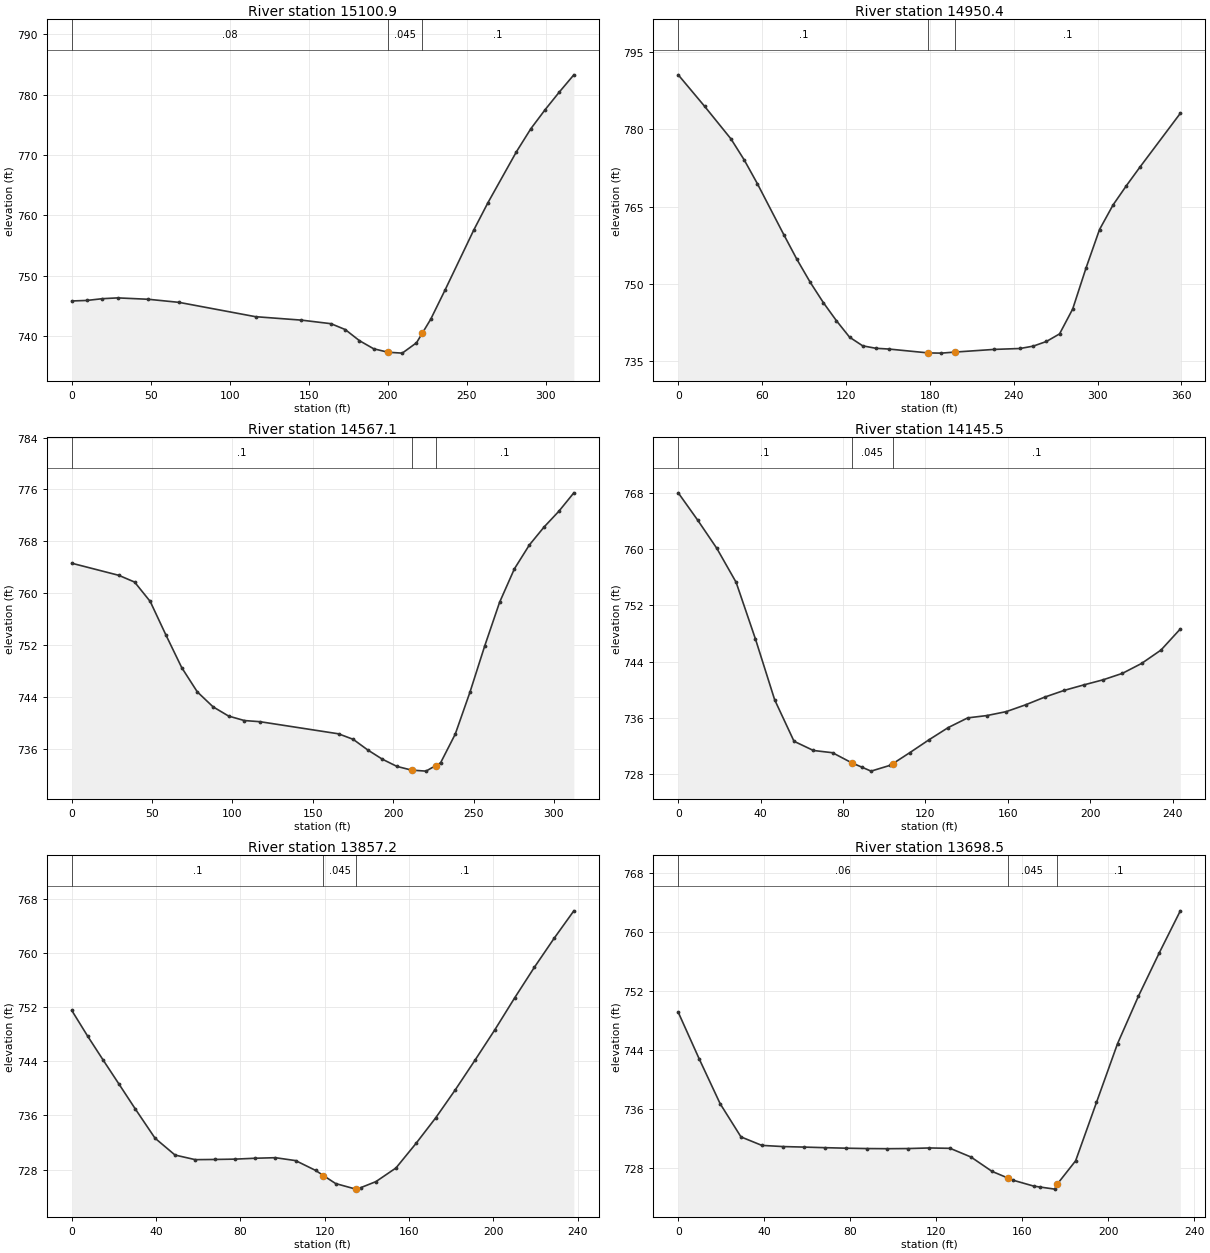
Type RM Length L Ch R = 1 ,15100.9 ,161.6,150.5,141.1
XS GIS Cut Line= 4
     1770464.243      470702.838     1770374.833      470829.574
     1770373.097      470901.622     1770387.854      470991.032
#Sta/Elev= 25
       0  745.85     9.7  745.94    19.4  746.23    29.1  746.36    48.5  746.13
    67.9  745.62   116.3  743.25   145.4  742.68   164.1  742.09   173.1  741.12
   182.1  739.28   191.1  737.94   200.1  737.37   209.2  737.22   218.2  738.93
   221.9  740.53   227.2  742.83   236.2  747.62   254.4  757.56   263.4   762.1
   281.5  770.56   290.6  774.36   299.7  777.53   308.7  780.45   317.8  783.27
#Mann= 3 , 0 , 0
       0     .08       0   200.1    .045       0   221.9      .1       0
Bank Sta=200.1,221.9
XS Rating Curve= 0 ,0
Exp/Cntr=0.3,0.1

Type RM Length L Ch R = 1 ,14950.4 ,388,383.3,378.5
XS GIS Cut Line= 4
     1770128.522      470705.659     1770196.014      470796.588
      1770260.25      470952.838     1770279.347       471027.49
#Sta/Elev= 29
       0   790.6    18.9  784.48    37.8  778.14    47.2  774.09    56.6  769.49
    75.5   759.6    84.9   754.8    94.4  750.36   103.8  746.41   113.2  742.88
   122.6  739.69     132  738.01   141.4  737.54   150.8  737.39   178.9  736.64
   188.3   736.6   197.7   736.8   225.9  737.32   244.6   737.5     254  737.96
   263.4  738.86   272.8  740.33   282.2  745.16   291.8  753.16   301.4  760.58
   311.1  765.36   320.7  769.12   330.3  772.69   359.2  783.13
#Mann= 3 , 0 , 0
       0      .1       0   178.9    .045       0   197.7      .1       0
Bank Sta=178.9,197.7
XS Rating Curve= 0 ,0
Exp/Cntr=0.3,0.1

Type RM Length L Ch R = 1 ,14567.1 ,427.7,421.6,414.5
XS GIS Cut Line= 4
     1769829.043      470940.034     1769971.187      471025.754
      1770014.59      471083.914      1770045.84      471150.754
#Sta/Elev= 29
       0  764.61    29.3  762.74    39.1   761.7    48.8  758.71    58.6  753.52
    68.4   748.5    78.1  744.75    87.9  742.44    97.6  741.01   107.4  740.32
   117.2  740.14     166  738.27   175.1  737.42   184.1  735.79   193.2  734.36
   202.3  733.24   211.4  732.67   220.4  732.51   226.5  733.37   229.5   733.8
   238.6  738.22   247.8  744.73     257  751.88   266.2  758.58   275.4  763.74
   284.7  767.42   293.9  770.21   303.1  772.64   312.4  775.48
#Mann= 3 , 0 , 0
       0      .1       0   211.4    .045       0   226.5      .1       0
Bank Sta=211.4,226.5
XS Rating Curve= 0 ,0
Exp/Cntr=0.3,0.1

Type RM Length L Ch R = 1 ,14145.5 ,280.6,288.3,295.9
XS GIS Cut Line= 3
     1769632.646      471300.928     1769743.757      471386.865
     1769840.979      471421.588
#Sta/Elev= 29
       0  768.02     9.4  764.15    18.7  760.13    28.1  755.28    37.5  747.19
    46.8  738.56    56.2  732.65    65.6  731.34    74.9  731.02    84.3  729.57
    89.1  728.97    93.6   728.4     103  729.24   104.1  729.45   112.4  731.03
   121.7  732.86   131.1  734.61   140.5  735.98   149.8  736.31   159.2  736.87
   168.6  737.84     178  738.95   187.4   739.9   196.8  740.67   206.2   741.4
   215.6  742.32   224.9  743.73   234.3  745.63   243.7  748.64
#Mann= 3 , 0 , 0
       0      .1       0    84.3    .045       0   104.1      .1       0
Bank Sta=84.3,104.1
XS Rating Curve= 0 ,0
Exp/Cntr=0.3,0.1

Type RM Length L Ch R = 1 ,13857.2 ,162.1,158.6,155
XS GIS Cut Line= 4
     1769512.854      471507.525     1769524.139      471535.303
        1769604.      471642.074     1769637.854      471708.914
#Sta/Elev= 30
       0   751.5     7.5  747.72      15  744.12    22.5  740.58      30  737.02
    39.5  732.64      49  730.15    58.6  729.47    68.1   729.5    77.6  729.55
    87.1  729.68    96.6  729.76   106.2  729.33   115.7  727.88   119.4  727.12
   125.2  725.94   134.4  725.15   134.7  725.12  137.29  725.36   144.3  726.23
   153.8  728.24   163.3  731.86   172.7  735.66     182   739.8   191.4   744.2
   200.8  748.68   210.1  753.34   219.5  757.88   228.9  762.17   238.2   766.2
#Mann= 3 , 0 , 0
       0      .1       0   119.4    .045       0   134.7      .1       0
Bank Sta=119.4,134.7
XS Rating Curve= 0 ,0
Exp/Cntr=0.3,0.1

Type RM Length L Ch R = 1 ,13698.5 ,116.4,118.8,121.1
XS GIS Cut Line= 2
     1769379.825      471617.117     1769536.075      471790.728
#Sta/Elev= 28
       0  749.11     9.7  742.81    19.5  736.69    29.2  732.18    38.9  731.03
    48.7  730.87    58.4   730.8    68.1  730.72    77.9  730.65    87.6   730.6
    97.3  730.58     107   730.6   116.8  730.68   126.5  730.63   136.2  729.45
     146   727.5   153.2  726.62   155.7  726.31   165.4   725.5   168.2  725.38
   175.2  725.09  176.26  725.74   184.9  728.94   194.6  736.87   204.4  744.85
   214.1  751.28   223.8  757.17   233.6  762.88
#Mann= 3 , 0 , 0
       0     .06       0   153.2    .045       0  176.26      .1       0
Bank Sta=153.2,176.26
XS Rating Curve= 0 ,0
Exp/Cntr=0.3,0.1

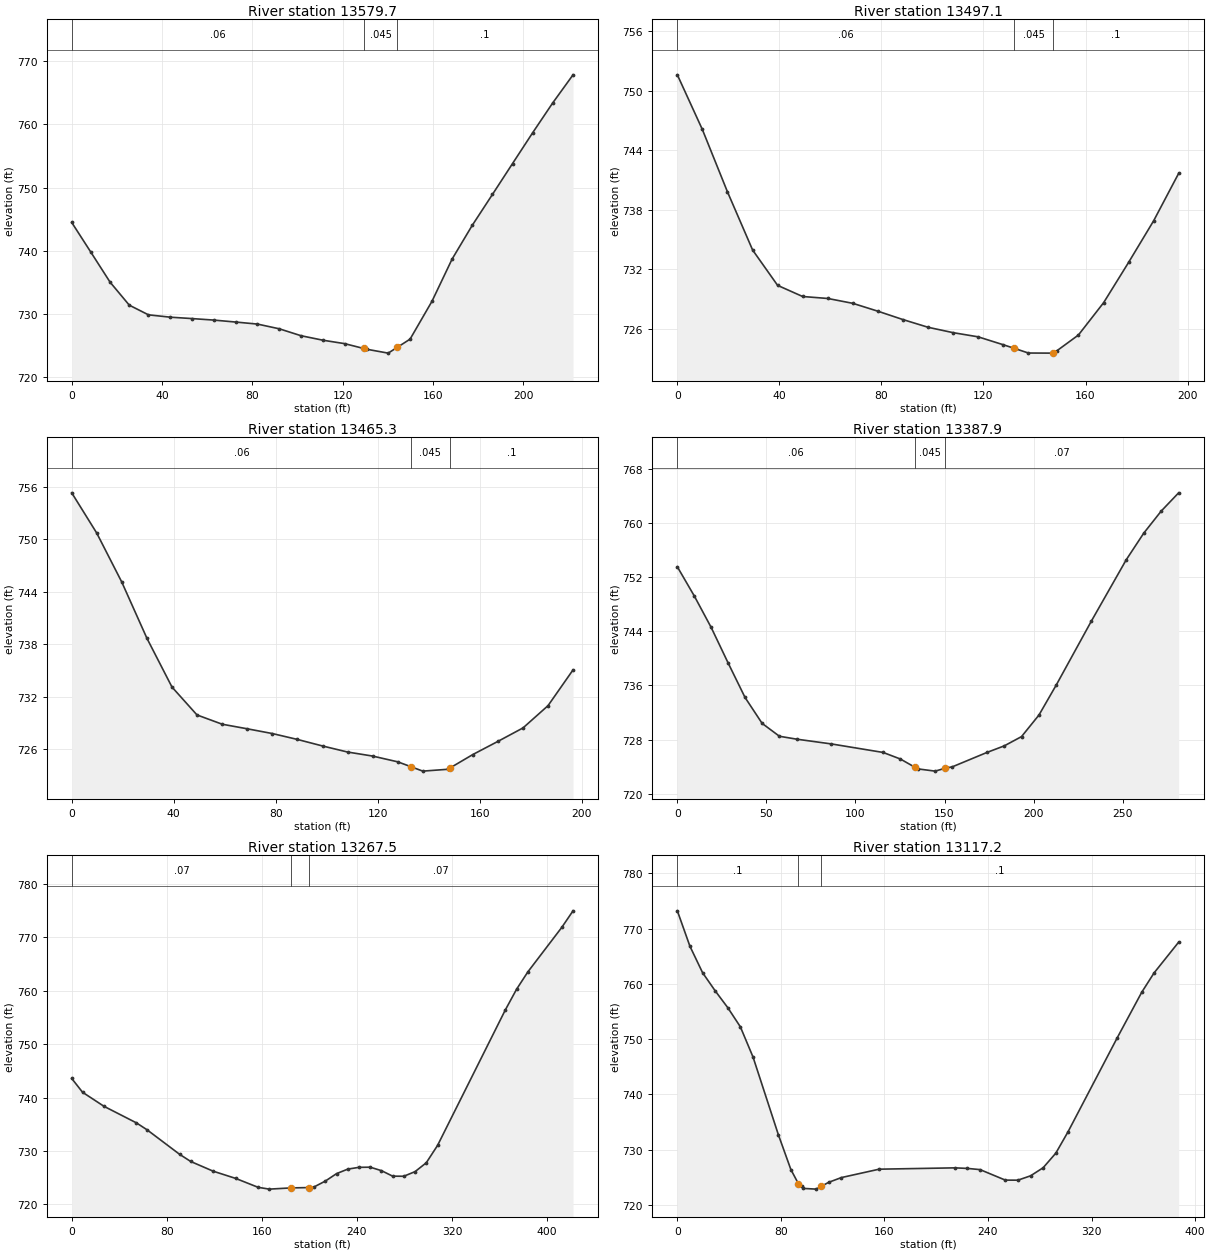
Type RM Length L Ch R = 1 ,13579.7 ,79.6,82.6,85.5
XS GIS Cut Line= 4
     1769310.597       471710.65     1769337.507      471731.483
     1769411.292      471833.046     1769439.937      471888.602
#Sta/Elev= 27
       0  744.49     8.5  739.78      17  735.05    25.5  731.42      34  729.89
    43.7  729.52    53.3   729.3      63  729.06    72.7  728.75    82.3  728.43
      92  727.68   101.6  726.59   111.3  725.88   120.9  725.34   129.3  724.58
   130.6  724.46   140.2  723.84   144.3  724.77   149.9  726.05   159.6  732.03
   168.5  738.69   177.4  744.01   186.4  748.92   195.3   753.8   204.2  758.66
   213.1  763.38   222.1  767.82
#Mann= 3 , 0 , 0
       0     .06       0   129.3    .045       0   144.3      .1       0
Bank Sta=129.3,144.3
XS Rating Curve= 0 ,0
Exp/Cntr=0.3,0.1

Type RM Length L Ch R = 1 ,13497.1 ,31.8,31.8,31.8
XS GIS Cut Line= 2
      1769260.25      471734.088        1769354.      471906.831
#Sta/Elev= 24
       0  751.59     9.8  746.09    19.6  739.84    29.5  733.96    39.3   730.4
    49.1  729.28      59  729.08    68.8  728.59    78.6   727.8    88.4  726.96
    98.3  726.18   108.1  725.64   117.9  725.22   127.8  724.42   132.1  724.06
   137.6  723.59   147.1  723.58   147.4  723.58  148.63  723.79   157.2   725.4
   167.1  728.66   176.9  732.72   186.7   736.9   196.5  741.67
#Mann= 3 , 0 , 0
       0     .06       0   132.1    .045       0   147.4      .1       0
Bank Sta=132.1,147.4
XS Rating Curve= 0 ,0
Exp/Cntr=0.3,0.1

Type RM Length L Ch R = 1 ,13465.3 ,79.1,77.4,75.7
XS GIS Cut Line= 2
     1769231.604      471747.977     1769325.354       471920.72
#Sta/Elev= 23
       0  755.28     9.8  750.69    19.6  745.11    29.5  738.67    39.3  733.12
    49.1  729.94      59  728.88    68.8  728.36    78.6  727.82    88.4  727.15
    98.3   726.4   108.1  725.71   117.9  725.25   127.8  724.59   133.1  724.02
   137.6  723.53   147.4  723.74   148.1  723.86   157.2  725.42   167.1  726.93
   176.9  728.46   186.7     731   196.5  735.08
#Mann= 3 , 0 , 0
       0     .06       0   133.1    .045       0   148.1      .1       0
Bank Sta=133.1,148.1
XS Rating Curve= 0 ,0
Exp/Cntr=0.3,0.1

Type RM Length L Ch R = 1 ,13387.9 ,151.5,120.4,96.1
XS GIS Cut Line= 4
     1769163.896      471787.907     1769181.257      471832.178
      1769260.25      471954.574     1769333.167      472004.053
#Sta/Elev= 26
       0  753.51     9.5  749.21      19  744.55    28.5  739.31      38  734.21
    47.6  730.38    57.3  728.48      67  728.05    86.4  727.35   115.5  726.09
   125.2  725.12   133.3  723.91     135  723.66   144.7  723.33   150.4  723.76
   154.4  723.97   173.8  726.09   183.5  727.06   193.2  728.43     203  731.62
   212.8   736.1   232.4  745.49     252  754.56   261.8  758.48   271.6  761.74
   281.4  764.44
#Mann= 3 , 0 , 0
       0     .06       0   133.3    .045       0   150.4     .07       0
Bank Sta=133.3,150.4
XS Rating Curve= 0 ,0
Exp/Cntr=0.3,0.1

Type RM Length L Ch R = 1 ,13267.5 ,150.5,150.3,142.5
XS GIS Cut Line= 4
     1768968.583      471903.358     1769038.896       471960.65
     1769241.153      472007.525     1769361.812      472033.567
#Sta/Elev= 30
       0  743.57     9.1  740.99    27.2  738.35    54.4  735.26    63.5  733.94
    90.7  729.38   100.1  728.03     119  726.21   137.9  724.86   156.8  723.19
   166.2  722.85   184.6  723.08   199.6  723.14   203.9  723.26   213.4  724.36
   222.8  725.75   232.3   726.6   241.7  726.93   251.1  726.96   260.6  726.31
     270  725.28   279.4  725.26   288.9  726.13   298.3  727.78   307.8  731.03
   364.8  756.39   374.3  760.28   383.8  763.53   412.3  771.85   421.8  774.96
#Mann= 3 , 0 , 0
       0     .07       0   184.6    .045       0   199.6     .07       0
Bank Sta=184.6,199.6
XS Rating Curve= 0 ,0
Exp/Cntr=0.3,0.1

Type RM Length L Ch R = 1 ,13117.2 ,188,184.6,181.2
XS GIS Cut Line= 3
     1768967.498      472114.079     1769245.276      472022.933
     1769338.592      472040.294
#Sta/Elev= 30
       0  773.22     9.7  766.82    19.5  762.02    29.2  758.75      39  755.68
    48.7  752.22    58.5  746.74      78  732.73    87.7   726.4   93.53  723.83
    96.3  723.37    97.4  722.98   107.2  722.85   111.3  723.37   116.9  724.08
   126.7  724.94   155.9  726.46   214.4   726.7   224.1   726.6   233.9  726.38
   253.4  724.48   263.1  724.47   272.9  725.26   282.6  726.72   292.4  729.36
   301.8  733.21   339.8  750.22   358.8  758.49   368.3  761.98   387.3  767.55
#Mann= 3 , 0 , 0
       0      .1       0   93.53    .045       0   111.3      .1       0
Bank Sta=93.53,111.3
XS Rating Curve= 0 ,0
Exp/Cntr=0.3,0.1

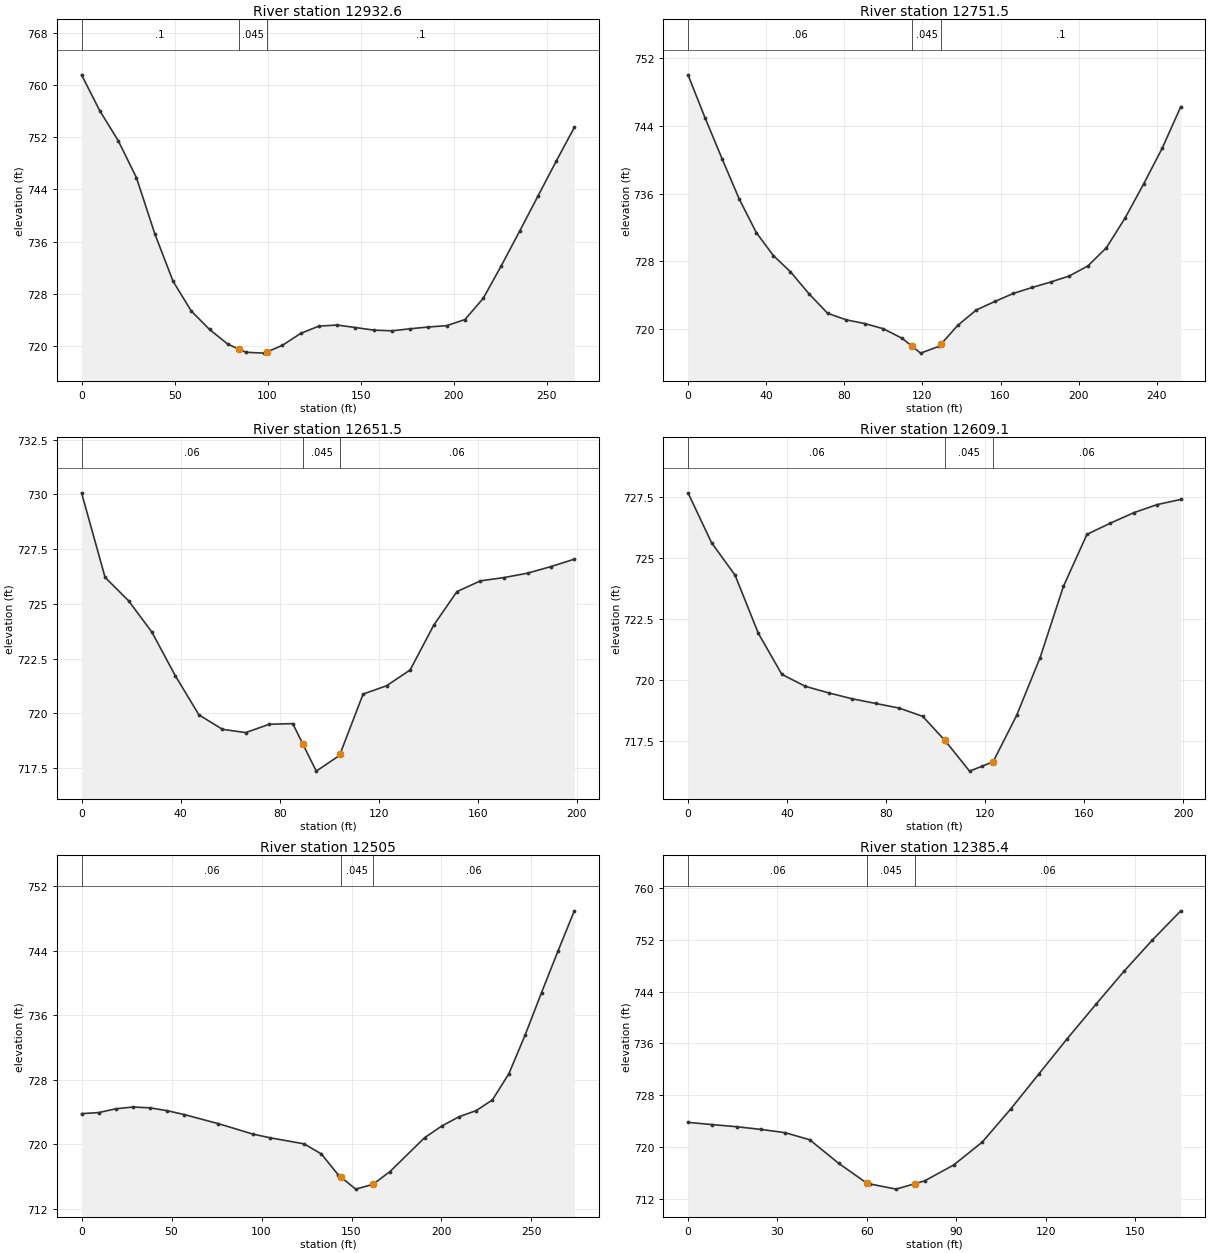
Type RM Length L Ch R = 1 ,12932.6 ,183.3,181.1,178.7
XS GIS Cut Line= 3
     1769110.944       472273.15     1769155.215      472234.088
     1769336.639      472136.865
#Sta/Elev= 30
       0  761.53     9.8  756.03    19.7  751.46    29.5  745.79    39.4  737.18
    49.2  729.92      59  725.36    68.8  722.55    78.6   720.3    84.6  719.53
    88.4  719.05    98.2  718.92    99.6  719.09     108  720.12   117.8  721.94
   127.6  723.06   137.4  723.22   147.2  722.84   157.1  722.44   166.9  722.34
   176.7  722.65   186.5  722.92   196.3  723.13   206.1  724.06   215.9   727.3
   225.7  732.33   235.5  737.59   245.3  742.94   255.1  748.27   264.9  753.48
#Mann= 3 , 0 , 0
       0      .1       0    84.6    .045       0    99.6      .1       0
Bank Sta=84.6,99.6
XS Rating Curve= 0 ,0
Exp/Cntr=0.3,0.1

Type RM Length L Ch R = 1 ,12751.5 ,88.1,100,111.9
XS GIS Cut Line= 3
     1769202.958      472390.338     1769254.174      472379.053
     1769422.576      472271.414
#Sta/Elev= 30
       0  749.97     8.7  744.92    17.5  740.06    26.2  735.36      35  731.39
    43.7  728.69    52.4   726.8      62  724.18    71.5   721.9      81  721.13
    90.5  720.69     100  720.08   109.6  718.96   114.6  718.04   119.1  717.21
   128.6  718.02   129.6  718.28   138.1  720.48   147.6  722.29   157.1  723.29
   166.6  724.24   176.2  724.94   185.7  725.58   195.2  726.29   204.7  727.47
   214.2  729.61   223.8  733.12   233.3  737.13   242.8  741.34   252.3  746.22
#Mann= 3 , 0 , 0
       0     .06       0   114.6    .045       0   129.6      .1       0
Bank Sta=114.6,129.6
XS Rating Curve= 0 ,0
Exp/Cntr=0.3,0.1

Type RM Length L Ch R = 1 ,12651.5 ,42.4,42.4,42.4
XS GIS Cut Line= 2
     1769235.076      472444.157     1769433.861      472434.608
#Sta/Elev= 24
       0  730.07     9.5  726.21      19  725.14    28.4  723.71    37.9  721.71
    47.4  719.93    56.9  719.27    66.3  719.12    75.8   719.5    85.3  719.53
    89.4  718.59    94.8  717.36   104.2  718.08   104.4  718.14   113.7  720.88
   123.2  721.26   132.7  721.98   142.2  724.02   151.6  725.56   161.1  726.05
   170.6   726.2   180.1   726.4   189.5   726.7     199  727.04
#Mann= 3 , 0 , 0
       0     .06       0    89.4    .045       0   104.4     .06       0
Bank Sta=89.4,104.4
XS Rating Curve= 0 ,0
Exp/Cntr=0.3,0.1

Type RM Length L Ch R = 1 ,12609.1 ,107.9,104.1,100.2
XS GIS Cut Line= 2
     1769231.604      472485.824     1769430.389      472476.275
#Sta/Elev= 24
       0  727.67     9.5  725.63      19   724.3    28.4  721.92    37.9  720.24
    47.4  719.75    56.9  719.48    66.3  719.24    75.8  719.05    85.3  718.86
    94.8  718.52   103.7  717.54   104.2  717.48   113.7  716.28   118.7  716.48
   123.2  716.66   132.7  718.56   142.2  720.93   151.6  723.84   161.1  725.97
   170.6  726.43   180.1  726.86   189.5  727.19     199   727.4
#Mann= 3 , 0 , 0
       0     .06       0   103.7    .045       0   123.2     .06       0
Bank Sta=103.7,123.2
XS Rating Curve= 0 ,0
Exp/Cntr=0.3,0.1

Type RM Length L Ch R = 1 ,12505   ,90.4,119.7,148.9
XS GIS Cut Line= 4
     1769200.354      472582.178     1769314.069      472590.858
     1769417.368      472570.893     1769471.187      472579.574
#Sta/Elev= 27
       0  723.82     9.5  723.95      19  724.42    28.5  724.64      38  724.54
    47.5  724.19      57  723.71      76  722.58      95   721.3   104.5  720.84
   123.6  720.08   133.2  718.84   142.7  716.22   144.2  715.95   152.3  714.47
   161.9  715.06   171.4  716.65   190.6  720.84   200.1  722.28   209.7  723.43
   219.3   724.2   228.3  725.52   237.4  728.75   246.5  733.57   255.6  738.82
   264.7  743.94   273.8  748.94
#Mann= 3 , 0 , 0
       0     .06       0   144.2    .045       0   161.9     .06       0
Bank Sta=144.2,161.9
XS Rating Curve= 0 ,0
Exp/Cntr=0.3,0.1

Type RM Length L Ch R = 1 ,12385.4 ,68.7,68.3,67.9
XS GIS Cut Line= 4
     1769232.472      472604.747     1769257.646      472636.865
     1769286.292      472687.213     1769320.146      472744.504
#Sta/Elev= 21
       0  723.86     8.2  723.51    16.3  723.19    24.5  722.77    32.6  722.27
    40.8  721.18    50.5  717.57    60.1  714.46    61.2  714.36    69.8  713.58
    76.2  714.43    79.4  714.86    89.1  717.29    98.7  720.82   108.2  725.89
   117.8  731.37   127.2  736.74   136.8  742.01   146.3  747.14   155.8  751.94
   165.3  756.42
#Mann= 3 , 0 , 0
       0     .06       0    60.1    .045       0    76.2     .06       0
Bank Sta=60.1,76.2
XS Rating Curve= 0 ,0
Exp/Cntr=0.3,0.1

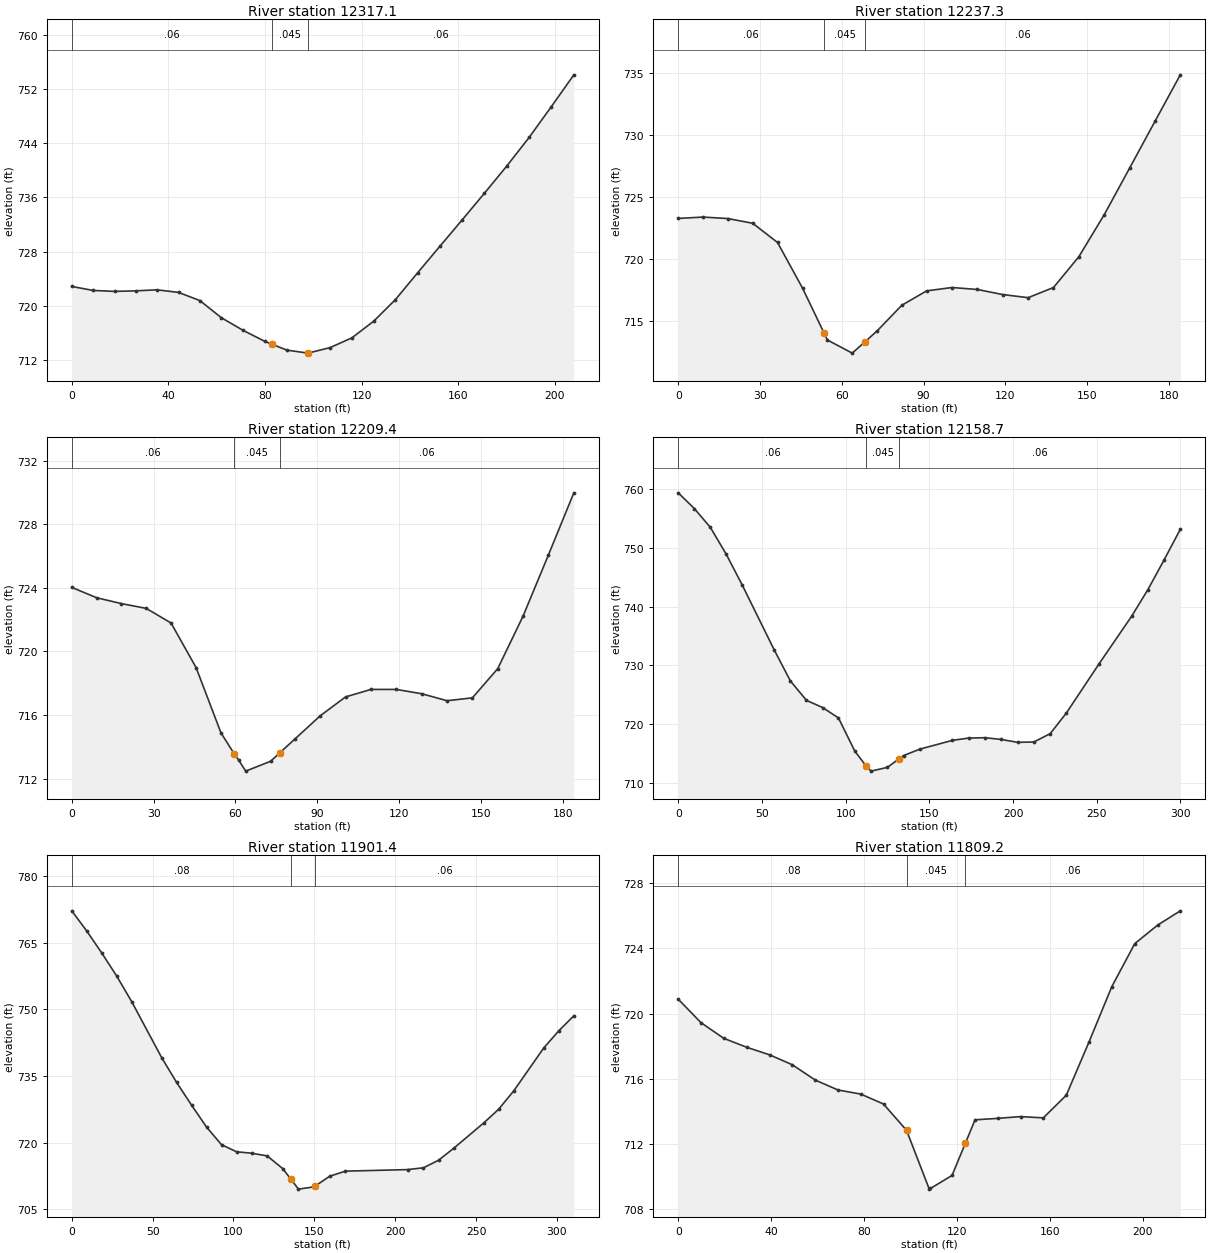
Type RM Length L Ch R = 1 ,12317.1 ,64.1,79.8,95
XS GIS Cut Line= 4
     1769157.819        472616.9     1769191.674      472657.699
      1769233.34      472727.143     1769269.799      472791.379
#Sta/Elev= 25
       0  722.86     8.8  722.27    17.7  722.13    26.5  722.21    35.3  722.36
    44.2  721.98      53  720.78      62  718.23      71  716.36      80  714.74
    82.8  714.34      89  713.46    97.8  713.01     107  713.83     116  715.27
     125  717.72     134  720.91   143.2  724.87   152.5  728.82   161.7  732.71
   170.9  736.64   180.2  740.68   189.4  744.88   198.6  749.43   207.9  754.12
#Mann= 3 , 0 , 0
       0     .06       0    82.8    .045       0    97.8     .06       0
Bank Sta=82.8,97.8
XS Rating Curve= 0 ,0
Exp/Cntr=0.3,0.1

Type RM Length L Ch R = 1 ,12237.3 ,25.2,27.9,26.6
XS GIS Cut Line= 3
     1769145.667      472634.261     1769133.514      472724.539
     1769181.257        472804.4
#Sta/Elev= 23
       0  723.26     9.1  723.37    18.2  723.25    27.3  722.87    36.4  721.32
    45.6  717.62    53.5  713.99    54.7  713.44    63.8  712.38    68.5   713.3
    72.9  714.17      82  716.25    91.1  717.41   100.4  717.68   109.7  717.52
     119  717.11   128.3  716.86   137.6  717.68   146.9  720.17   156.2  723.56
   165.5  727.32   174.8   731.1   184.1  734.86
#Mann= 3 , 0 , 0
       0     .06       0    53.5    .045       0    68.5     .06       0
Bank Sta=53.5,68.5
XS Rating Curve= 0 ,0
Exp/Cntr=0.3,0.1

Type RM Length L Ch R = 1 ,12209.4 ,71.9,50.7,33.2
XS GIS Cut Line= 3
     1769121.361      472635.997     1769109.208      472726.275
     1769156.951      472806.136
#Sta/Elev= 24
       0  724.03     9.1  723.38    18.2  723.01    27.3  722.71    36.4  721.79
    45.6  718.98    54.7  714.88   59.52  713.57    61.2  713.16    63.8  712.47
    72.9  713.09    76.2  713.61      82  714.52    91.1  715.95   100.4  717.14
   109.7  717.61     119  717.61   128.3  717.34   137.6   716.9   146.9  717.08
   156.2  718.92   165.5  722.23   174.8  726.08   184.1  729.98
#Mann= 3 , 0 , 0
       0     .06       0   59.52    .045       0    76.2     .06       0
Bank Sta=59.52,76.2
XS Rating Curve= 0 ,0
Exp/Cntr=0.3,0.1

Type RM Length L Ch R = 1 ,12158.7 ,265.1,257.2,249.4
XS GIS Cut Line= 3
     1769008.731      472608.871     1769046.708      472696.761
     1769171.708       472858.22
#Sta/Elev= 30
       0  759.38     9.6  756.71    19.2  753.49    28.7  748.91    38.3  743.64
    57.4   732.6      67  727.35    76.6  724.05    86.2  722.83    95.7  721.06
   105.5  715.39   112.4  712.81   115.2     712   124.9  712.64   131.7  714.05
   134.6  714.65   144.4  715.75   163.8  717.24   173.5  717.63   183.2  717.69
     193  717.39   202.7   716.9   212.4  716.96   222.2  718.38   231.9  721.92
   251.3  730.24   270.8  738.36   280.5  742.88   290.2  747.95   299.9  753.18
#Mann= 3 , 0 , 0
       0     .06       0   112.4    .045       0   131.7     .06       0
Bank Sta=112.4,131.7
XS Rating Curve= 0 ,0
Exp/Cntr=0.3,0.1

Type RM Length L Ch R = 1 ,11901.4 ,102.5,92.2,81.9
XS GIS Cut Line= 4
     1768796.057      472817.204      1768880.91      472889.036
     1768972.055      472943.723     1769058.644      472977.794
#Sta/Elev= 30
       0  772.18     9.3  767.62    18.5  762.71    27.8  757.48    37.1   751.7
    55.6  739.11    64.8  733.55    74.1  728.41    83.4  723.45    92.6  719.51
   101.9  717.91   111.2  717.59   120.8  716.99   130.5  714.12   135.6  711.69
   140.2   709.5   149.8  710.01   150.6  710.21   159.5   712.4   169.2  713.55
   207.8   713.9   217.5  714.31   226.8     716   236.1  718.67   254.7  724.38
     264  727.49   273.3  731.61   291.9   741.3   301.2  745.16   310.5  748.54
#Mann= 3 , 0 , 0
       0     .08       0   135.6    .045       0   150.6     .06       0
Bank Sta=135.6,150.6
XS Rating Curve= 0 ,0
Exp/Cntr=0.3,0.1

Type RM Length L Ch R = 1 ,11809.2 ,43.3,43.3,43.3
XS GIS Cut Line= 2
     1768780.215      472985.824     1768995.493      473005.789
#Sta/Elev= 25
       0  720.88     9.8  719.44    19.6  718.48    29.5  717.93    39.3  717.47
    49.1  716.86      59  715.92    68.8  715.31    78.6  715.06    88.4  714.45
    98.3  712.84   108.1  709.23   108.6  709.27   117.9  710.07   123.6  712.03
   127.8  713.48   137.6  713.57   147.4  713.68   157.2   713.6   167.1  714.99
   176.9  718.26   186.7  721.65   196.6  724.29   206.4  725.42   216.2   726.3
#Mann= 3 , 0 , 0
       0     .08       0    98.3    .045       0   123.6     .06       0
Bank Sta=98.3,123.6
XS Rating Curve= 0 ,0
Exp/Cntr=0.3,0.1

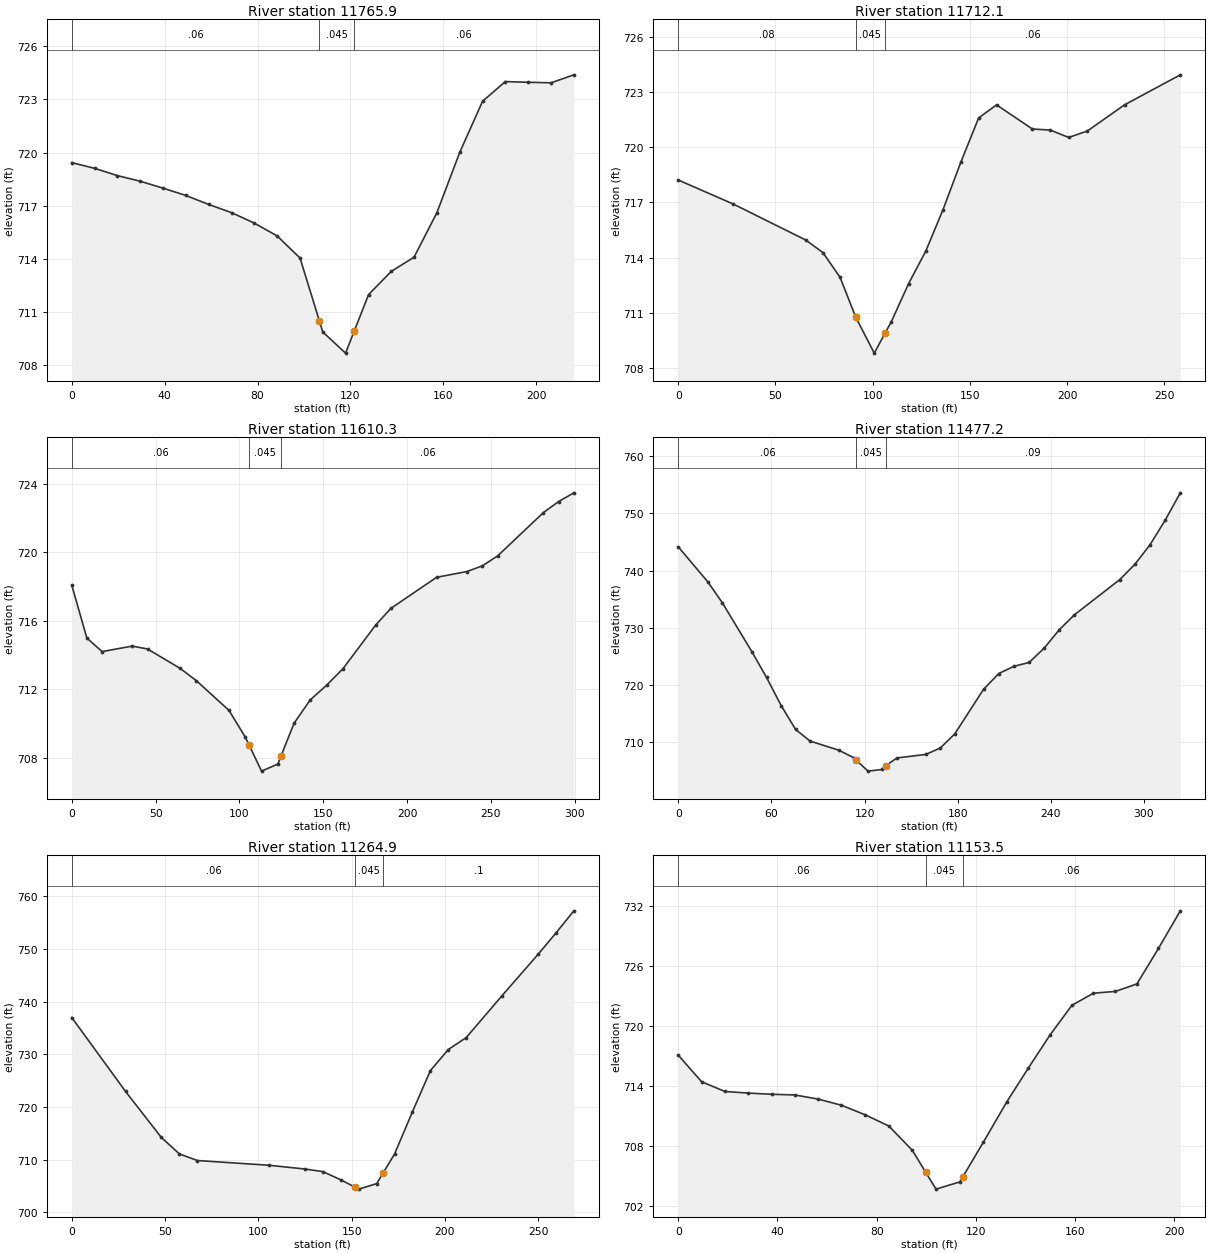
Type RM Length L Ch R = 1 ,11765.9 ,51.8,53.8,55.6
XS GIS Cut Line= 2
     1768779.347      473029.227     1768994.625      473049.192
#Sta/Elev= 25
       0  719.43     9.8  719.11    19.6   718.7    29.5  718.38    39.3  717.99
    49.1  717.58      59  717.07    68.8  716.61    78.6  716.02    88.4   715.3
    98.3  714.05   106.6  710.52   108.1  709.88   117.9  708.69   121.6  709.92
   127.8  711.99   137.6   713.3   147.4   714.1   157.2   716.6   167.1  720.02
   176.9  722.89   186.7     724   196.6  723.96   206.4  723.93   216.2  724.38
#Mann= 3 , 0 , 0
       0     .06       0   106.6    .045       0   121.6     .06       0
Bank Sta=106.6,121.6
XS Rating Curve= 0 ,0
Exp/Cntr=0.3,0.1

Type RM Length L Ch R = 1 ,11712.1 ,101.4,101.9,102.3
XS GIS Cut Line= 5
     1768794.972      473057.872     1768844.451       473085.65
     1768922.576      473099.539     1768972.924       473076.97
     1769038.896      473088.254
#Sta/Elev= 21
       0  718.21    28.4   716.9    65.6  714.95    74.4  714.27    83.2  712.93
    91.3  710.76   100.8  708.81   106.3  709.88   109.6  710.52   118.5  712.59
   127.3  714.35   136.1  716.58   145.3  719.17   154.5  721.58   163.7  722.29
   182.1  720.98   191.3  720.92   200.8  720.52   210.4  720.87   229.5  722.29
   258.2  723.92
#Mann= 3 , 0 , 0
       0     .08       0    91.3    .045       0   106.3     .06       0
Bank Sta=91.3,106.3
XS Rating Curve= 0 ,0
Exp/Cntr=0.3,0.1

Type RM Length L Ch R = 1 ,11610.3 ,136.1,133.1,130.1
XS GIS Cut Line= 4
     1768729.868      473171.588     1768775.007      473169.852
     1768908.687      473195.025     1769026.743      473202.838
#Sta/Elev= 26
       0  718.08       9  714.99    18.1   714.2    36.1  714.52    45.2  714.35
    64.6  713.22    74.3   712.5    93.8  710.76   103.5   709.2   105.8  708.73
   113.2  707.21   122.9  707.62  124.89  708.11   132.6  710.01   142.3  711.38
     152  712.23   161.8   713.2   181.2  715.74   190.3  716.72   217.6  718.54
   235.8  718.88   244.9  719.21     254  719.79   281.3  722.32   290.4  722.97
   299.5  723.48
#Mann= 3 , 0 , 0
       0     .06       0   105.8    .045       0  124.89     .06       0
Bank Sta=105.8,124.89
XS Rating Curve= 0 ,0
Exp/Cntr=0.3,0.1

Type RM Length L Ch R = 1 ,11477.2 ,194.4,212.2,230.1
XS GIS Cut Line= 4
      1768706.43      473318.289     1768772.403      473311.345
     1768902.611      473318.289     1769008.514      473387.733
#Sta/Elev= 30
       0  744.16      19  738.06    28.4  734.39    47.4  725.85    56.9  721.33
    66.3  716.42    75.6  712.25      85  710.21   103.6  708.61   112.9  707.33
   114.8  706.85   122.2  704.97   131.5  705.26  133.61  705.89   140.8  707.27
   159.5  707.89   168.8  709.01   178.1  711.47   196.7  719.28   206.5  722.02
   216.2  723.28     226  723.95   235.7  726.45   245.4  729.66   255.2  732.28
   284.4  738.43   294.2  741.12   303.9  744.52   313.6  748.78   323.4  753.59
#Mann= 3 , 0 , 0
       0     .06       0   114.8    .045       0  133.61     .09       0
Bank Sta=114.8,133.61
XS Rating Curve= 0 ,0
Exp/Cntr=0.3,0.1

Type RM Length L Ch R = 1 ,11264.9 ,109.7,111.4,112.9
XS GIS Cut Line= 2
     1768656.083       473393.81     1768838.375      473591.727
#Sta/Elev= 22
       0  736.96    28.8  722.94      48   714.2    57.7  711.07    67.3  709.82
   105.7  708.92   124.9  708.21   134.5  707.72   144.2  706.16   151.8  704.76
   153.8  704.39   163.4  705.43   166.8  707.42     173  711.05   182.6  719.07
   192.2  726.88   201.8  730.88   211.4  733.15   230.6   741.1   249.9  748.94
   259.5     753   269.1  757.21
#Mann= 3 , 0 , 0
       0     .06       0   151.8    .045       0   166.8      .1       0
Bank Sta=151.8,166.8
XS Rating Curve= 0 ,0
Exp/Cntr=0.3,0.1

Type RM Length L Ch R = 1 ,11153.5 ,31.5,34.1,36.7
XS GIS Cut Line= 4
     1768611.812      473503.185     1768655.215      473552.664
     1768696.882      473604.747     1768754.174      473644.678
#Sta/Elev= 25
       0  717.08     9.4  714.42    18.8  713.44    28.2  713.28    37.6  713.16
      47  713.09    56.4  712.68    65.8  712.06    75.4   711.1    84.9  709.98
    94.4  707.54    99.8  705.33   103.9  703.66   113.5  704.38   114.8  704.92
     123  708.36   132.5  712.42   141.2  715.81     150  719.14   158.7  722.07
   167.4  723.28   176.2  723.46   184.9  724.21   193.6  727.77   202.4  731.53
#Mann= 3 , 0 , 0
       0     .06       0    99.8    .045       0   114.8     .06       0
Bank Sta=99.8,114.8
XS Rating Curve= 0 ,0
Exp/Cntr=0.3,0.1