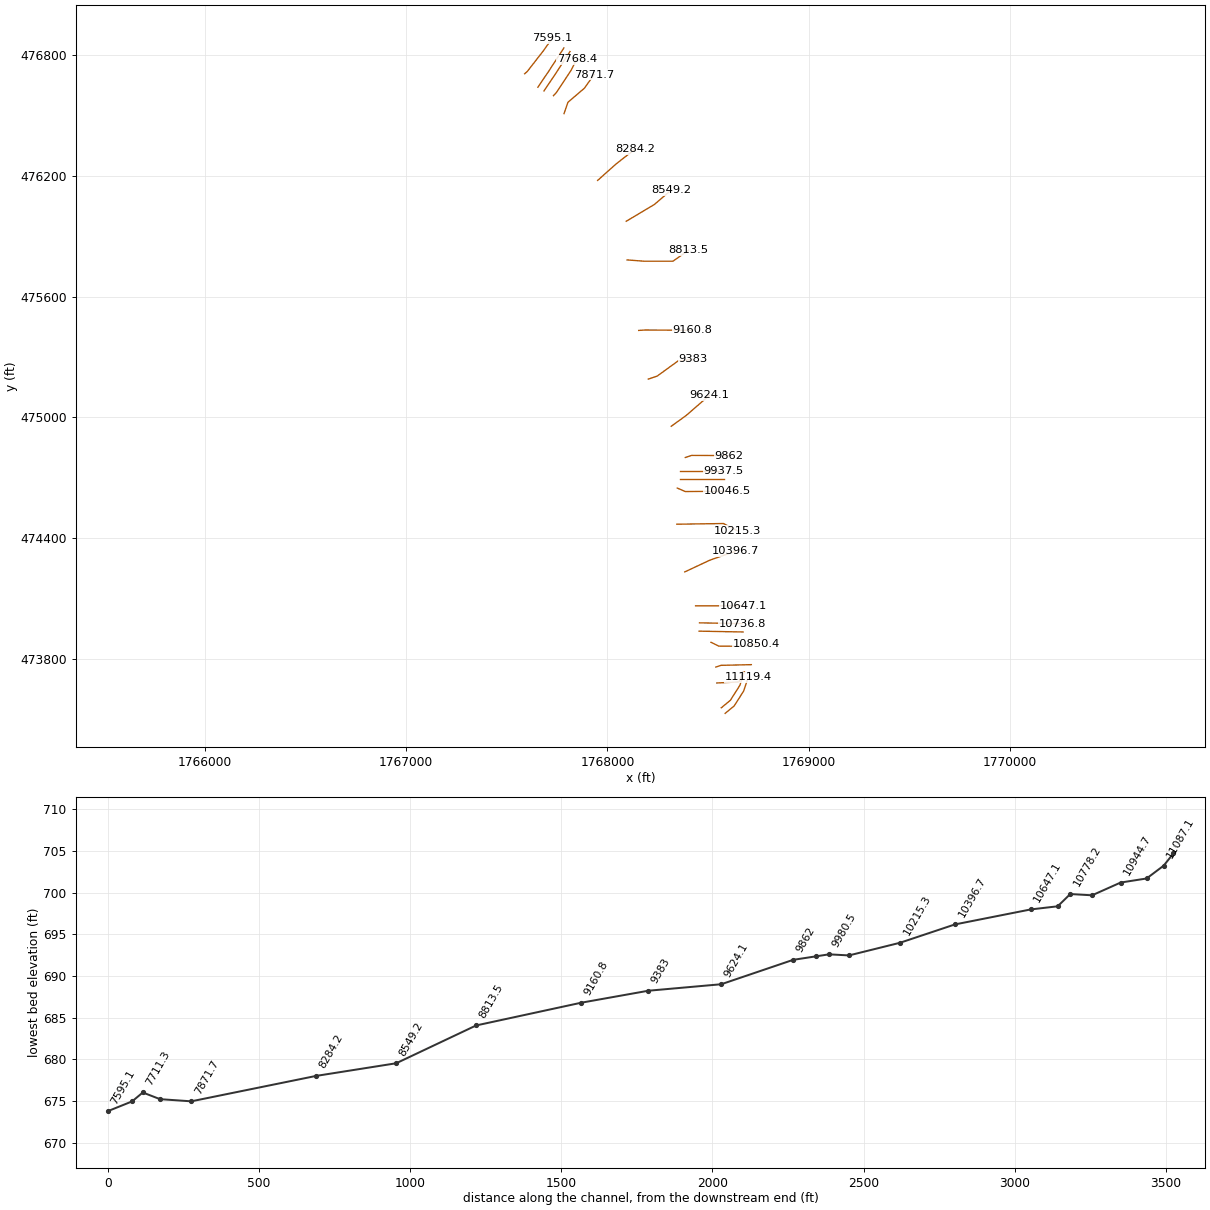
HEC-RAS study MIDFORK1.prj: MIDFORK1

--- MIDFORK1.g01 (geometry) --- (continued)

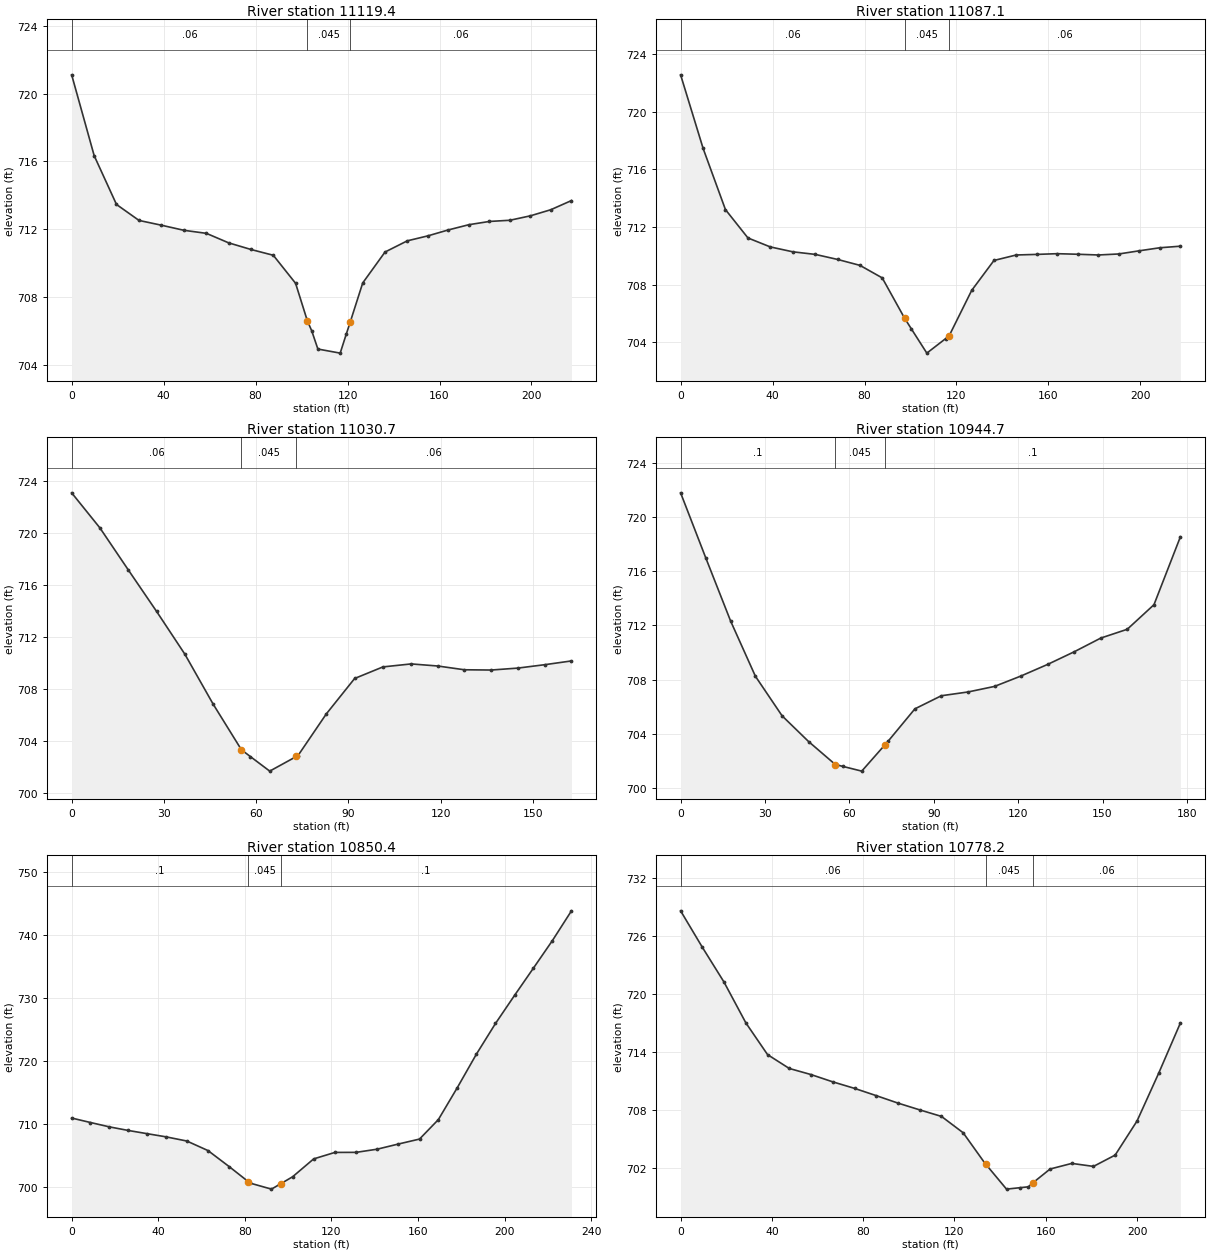
Type RM Length L Ch R = 1 ,11119.4 ,32.3,32.3,32.3
XS GIS Cut Line= 4
     1768584.903      473528.358     1768630.042      473565.685
     1768676.917       473639.47     1768699.486      473707.178
#Sta/Elev= 28
       0   721.1     9.8  716.34    19.5  713.47    29.3  712.53      39  712.25
    48.8  711.95    58.6  711.77    68.3  711.21      78  710.82    87.7  710.48
    97.4  708.83  102.52  706.62   104.4  706.04   107.1  704.96   116.8  704.72
   119.4  705.82  121.12  706.53   126.6  708.85   136.3  710.67     146  711.33
   154.9  711.62   163.8  711.97   172.8  712.28   181.7  712.47   190.6  712.54
   199.5   712.8   208.4  713.16   217.4   713.7
#Mann= 3 , 0 , 0
       0     .06       0  102.52    .045       0  121.12     .06       0
Bank Sta=102.52,121.12
XS Rating Curve= 0 ,0
Exp/Cntr=0.3,0.1

Type RM Length L Ch R = 1 ,11087.1 ,78.1,56.4,34
XS GIS Cut Line= 4
     1768565.805      473556.136     1768610.944      473593.463
     1768657.819      473667.247     1768680.389      473734.956
#Sta/Elev= 26
       0  722.56     9.8  717.45    19.5  713.21    29.3  711.24      39  710.62
    48.8  710.28    58.6   710.1    68.3  709.75      78  709.34    87.7  708.47
    97.4  705.68   100.3  704.95   107.1  703.25   115.3  704.26   116.8  704.45
   126.6   707.6   136.3  709.68     146  710.06   154.9   710.1   163.8  710.15
   172.8  710.11   181.7  710.06   190.6  710.13   199.5  710.35   208.4  710.56
   217.4  710.67
#Mann= 3 , 0 , 0
       0     .06       0    97.4    .045       0   116.8     .06       0
Bank Sta=97.4,116.8
XS Rating Curve= 0 ,0
Exp/Cntr=0.3,0.1

Type RM Length L Ch R = 1 ,11030.7 ,86.5,86,85.7
XS GIS Cut Line= 3
     1768543.236        473679.4     1768653.479      473684.608
     1768674.312      473732.352
#Sta/Elev= 21
       0   723.1     9.2   720.4    18.4  717.18    27.6  713.99    36.8   710.7
      46  706.86    55.2  703.35    58.1  702.83    64.4  701.71    73.1  702.84
    73.6  702.91    82.8  706.11      92  708.83   101.2  709.72   110.4  709.95
     119  709.79   127.7   709.5   136.4  709.48   145.1  709.63   153.8  709.89
   162.5  710.18
#Mann= 3 , 0 , 0
       0     .06       0    55.2    .045       0    73.1     .06       0
Bank Sta=55.2,73.1
XS Rating Curve= 0 ,0
Exp/Cntr=0.3,0.1

Type RM Length L Ch R = 1 ,10944.7 ,95,94.3,93.7
XS GIS Cut Line= 3
     1768538.896      473758.393     1768564.069      473767.074
     1768715.111      473770.546
#Sta/Elev= 22
       0  721.82     8.9  717.03    17.8  712.32    26.6  708.24    36.1  705.31
    45.5  703.41      55  701.71    57.7  701.57    64.4  701.22    72.7  703.18
    73.8  703.44    83.3  705.83    92.7   706.8   102.2  707.08   111.6  707.49
     121  708.26   130.5  709.12   139.9  710.05   149.4  711.07   158.8  711.72
   168.3  713.54   177.7  718.57
#Mann= 3 , 0 , 0
       0      .1       0      55    .045       0    72.7      .1       0
Bank Sta=55,72.7
XS Rating Curve= 0 ,0
Exp/Cntr=0.3,0.1

Type RM Length L Ch R = 1 ,10850.4 ,72.4,72.2,71.9
XS GIS Cut Line= 4
      1768514.59      473881.657     1768553.653       473862.56
      1768670.84      473861.692     1768740.285      473872.108
#Sta/Elev= 28
       0  710.98     8.7  710.27    17.4  709.58    26.1  709.01    34.8   708.5
    43.5     708    53.2  707.33      63  705.81    72.8  703.26    81.6  700.88
    82.5  700.64    92.3  699.69    96.6  700.55   102.1  701.66   111.8  704.49
   121.6  705.52   131.4  705.53   141.1  706.03   150.9  706.85   160.7  707.64
   169.4  710.73   178.2  715.83     187  721.14   195.8     726   204.6  730.46
   213.3  734.78   222.1  739.17   230.9  743.89
#Mann= 3 , 0 , 0
       0      .1       0    81.6    .045       0    96.6      .1       0
Bank Sta=81.6,96.6
XS Rating Curve= 0 ,0
Exp/Cntr=0.3,0.1

Type RM Length L Ch R = 1 ,10778.2 ,41.4,41.5,41.5
XS GIS Cut Line= 2
     1768455.345      473936.996     1768674.312      473932.872
#Sta/Elev= 27
       0  728.62     9.5  724.86      19  721.26    28.6  717.03    38.1  713.75
    47.6  712.32    57.1  711.69    66.6  710.94    76.2  710.26    85.7  709.51
    95.2  708.74   104.7  708.04   114.3  707.36   123.8  705.67   133.3  702.53
   133.8  702.39   142.8  699.84   148.8  699.99   152.4  700.08  154.34  700.49
   161.9  701.92   171.4   702.5   180.9  702.19   190.4  703.36     200  706.89
   209.5  711.84     219  717.03
#Mann= 3 , 0 , 0
       0     .06       0   133.8    .045       0  154.34     .06       0
Bank Sta=133.8,154.34
XS Rating Curve= 0 ,0
Exp/Cntr=0.3,0.1

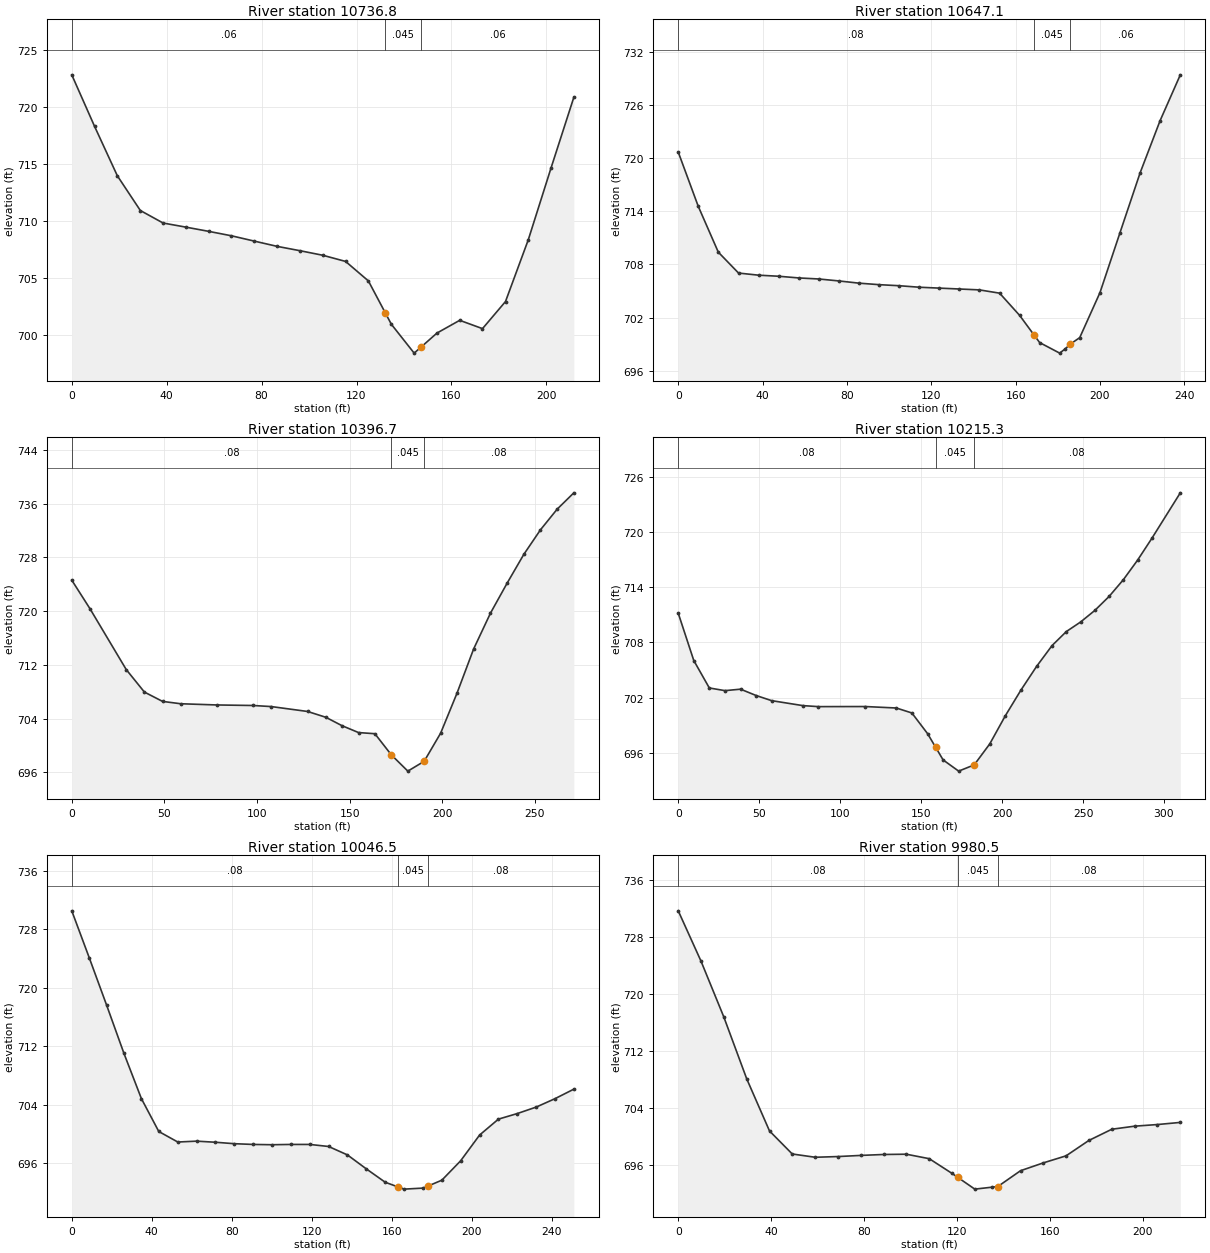
Type RM Length L Ch R = 1 ,10736.8 ,88.9,89.6,90
XS GIS Cut Line= 2
     1768457.516      473978.228     1768669.104      473974.539
#Sta/Elev= 25
       0   722.8     9.6  718.28    19.2  713.94    28.9  710.89    38.5  709.79
    48.1  709.43    57.7  709.06    67.3  708.67      77   708.2    86.6  707.74
    96.2  707.36   105.8  706.96   115.4  706.42     125  704.71   132.1  701.92
   134.7   700.9   144.3  698.37   147.1  698.88   153.9  700.13   163.5  701.25
   173.1  700.52   182.8   702.9   192.4  708.32     202  714.63   211.6  720.83
#Mann= 3 , 0 , 0
       0     .06       0   132.1    .045       0   147.1     .06       0
Bank Sta=132.1,147.1
XS Rating Curve= 0 ,0
Exp/Cntr=0.3,0.1

Type RM Length L Ch R = 1 ,10647.1 ,242.8,250.4,258
XS GIS Cut Line= 2
     1768437.984      474062.864     1768676.049      474063.081
#Sta/Elev= 29
       0  720.69     9.5  714.56      19  709.39    28.6  707.03    38.1  706.79
    47.6  706.67    57.1  706.48    66.7  706.36    76.2  706.14    85.7  705.89
    95.2  705.72   104.8   705.6   114.3  705.43   123.8  705.33   133.3  705.23
   142.8  705.13   152.4  704.76   161.9  702.25   168.6  700.08   171.4  699.18
   180.9  697.99   183.6  698.49  186.01  699.02   190.4  699.74     200  704.82
   209.5  711.59     219  718.32   228.5  724.23   238.1  729.41
#Mann= 3 , 0 , 0
       0     .08       0   168.6    .045       0  186.01     .06       0
Bank Sta=168.6,186.01
XS Rating Curve= 0 ,0
Exp/Cntr=0.3,0.1

Type RM Length L Ch R = 1 ,10396.7 ,188.5,181.4,174.6
XS GIS Cut Line= 4
     1768384.382      474231.483     1768508.514      474289.643
     1768575.354      474313.081      1768635.25      474333.046
#Sta/Elev= 26
       0  724.62     9.8  720.38    29.4  711.31    39.2  707.96      49  706.57
    58.8  706.22    78.3  706.04    97.9  705.96   107.7   705.8   127.3  705.07
   137.1  704.21   145.9  702.95   154.8  701.93   163.6  701.76   172.5  698.61
   181.4  696.19   190.2  697.65   199.1  701.84   207.9  707.77   216.9  714.37
     226  719.71     235  724.18     244  728.46     253  732.12     262  735.19
     271  737.62
#Mann= 3 , 0 , 0
       0     .08       0   172.5    .045       0   190.2     .08       0
Bank Sta=172.5,190.2
XS Rating Curve= 0 ,0
Exp/Cntr=0.3,0.1

Type RM Length L Ch R = 1 ,10215.3 ,170,168.8,167.4
XS GIS Cut Line= 3
     1768345.319      474468.463     1768576.222      474471.935
     1768646.535      474435.477
#Sta/Elev= 30
       0  711.18     9.6  706.03    19.2  703.04    28.9  702.75    38.5  702.91
    48.1  702.22    57.7  701.66      77  701.12    86.6  701.01   115.5  701.02
   134.7  700.86   144.3  700.32     154  698.07     159  696.58   163.6  695.21
   173.2  693.99   182.8  694.67   192.4  696.95   202.1  700.04   211.7  702.82
   221.3  705.38   230.9  707.66   239.7  709.18   248.5  710.22   257.3  711.48
   266.1     713   274.9  714.82   283.7  716.95   292.5  719.32   310.1  724.28
#Mann= 3 , 0 , 0
       0     .08       0     159    .045       0   182.8     .08       0
Bank Sta=159,182.8
XS Rating Curve= 0 ,0
Exp/Cntr=0.3,0.1

Type RM Length L Ch R = 1 ,10046.5 ,66.2,66,65.5
XS GIS Cut Line= 3
     1768347.055       474648.15     1768386.986      474630.789
     1768594.451      474632.525
#Sta/Elev= 30
       0  730.52     8.7  724.13    17.4  717.64    26.1  711.02    34.8  704.85
    43.5  700.35      53  698.91    62.4  699.03    71.8  698.88    81.3  698.68
    90.7  698.58   100.1  698.54   109.6  698.58     119  698.58   128.4   698.3
   137.8  697.15   147.3  695.23   156.7  693.41   162.9  692.79   166.1  692.47
   175.6  692.61   177.9  692.87     185  693.69   194.4  696.34   203.9  699.87
   213.3  702.04   222.7   702.8   232.2  703.69   241.6  704.84     251  706.14
#Mann= 3 , 0 , 0
       0     .08       0   162.9    .045       0   177.9     .08       0
Bank Sta=162.9,177.9
XS Rating Curve= 0 ,0
Exp/Cntr=0.3,0.1

Type RM Length L Ch R = 1 ,9980.5  ,42.7,43,43.3
XS GIS Cut Line= 2
     1768361.812      474693.289     1768577.958      474693.289
#Sta/Elev= 25
       0  731.73     9.8  724.66    19.6  716.83    29.5   708.1    39.3  700.78
    49.1  697.54      59  697.08    68.8  697.18    78.6  697.34    88.4  697.47
    98.2  697.51   108.1  696.88   117.9  694.81   120.3  694.27   127.7   692.6
   135.3  692.88   137.6  692.96   147.4  695.19   157.2  696.29     167  697.28
   176.8  699.44   186.7  701.02   196.5  701.45   206.3  701.68   216.2  701.98
#Mann= 3 , 0 , 0
       0     .08       0   120.3    .045       0   137.6     .08       0
Bank Sta=120.3,137.6
XS Rating Curve= 0 ,0
Exp/Cntr=0.3,0.1

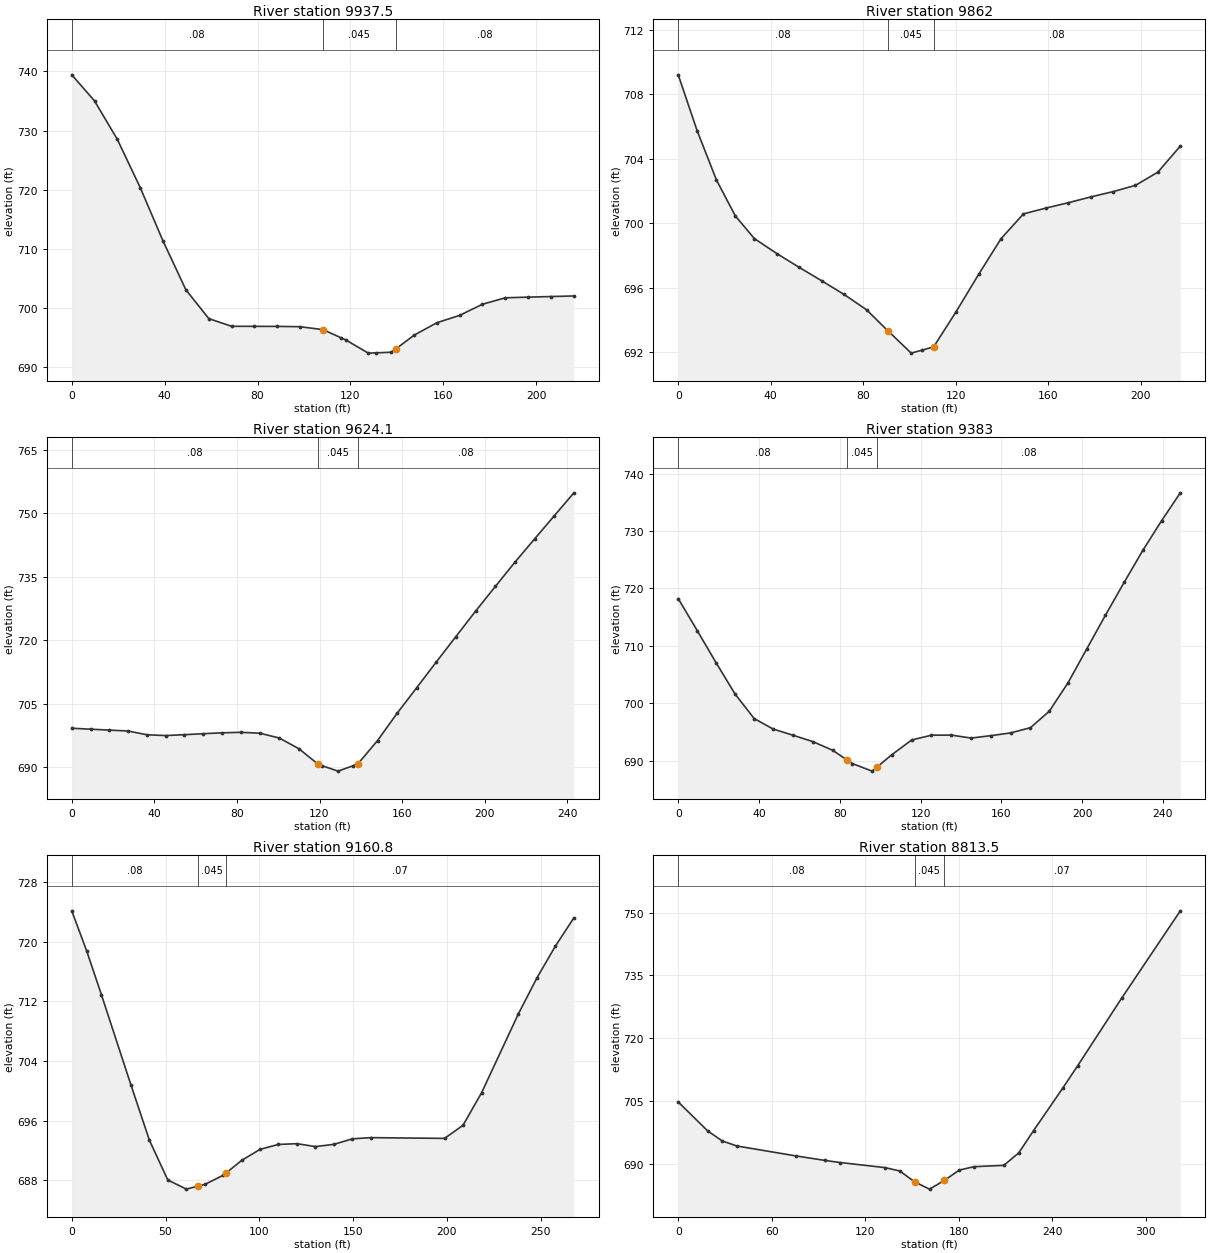
Type RM Length L Ch R = 1 ,9937.5  ,75.6,75.5,75.4
XS GIS Cut Line= 2
     1768360.076      474734.956     1768576.222      474734.956
#Sta/Elev= 26
       0  739.43     9.8  735.02    19.6  728.53    29.5  720.34    39.3  711.33
    49.1   703.1      59   698.2    68.8   696.9    78.6  696.89    88.4  696.88
    98.2  696.83   108.1  696.34     116  694.95   117.9  694.61   127.7  692.36
     131  692.41   137.6  692.51   139.5  693.06   147.4  695.39   157.2   697.5
     167  698.74   176.8  700.62   186.7  701.72   196.5  701.83   206.3  701.93
   216.2  702.03
#Mann= 3 , 0 , 0
       0     .08       0   108.1    .045       0   139.5     .08       0
Bank Sta=108.1,139.5
XS Rating Curve= 0 ,0
Exp/Cntr=0.3,0.1

Type RM Length L Ch R = 1 ,9862    ,221.4,237.8,254
XS GIS Cut Line= 3
     1768386.986       474800.06     1768418.236      474810.477
     1768602.264      474809.608
#Sta/Elev= 26
       0  709.21     8.2  705.73    16.5  702.69    24.7  700.45    32.9  699.05
    42.6  698.12    52.3  697.26      62  696.43    71.7  695.58    81.4  694.63
    90.5  693.34    91.1  693.26   100.7  691.94   105.5  692.13   110.4  692.33
   120.1  694.51   129.8  696.82   139.5  699.04   149.2  700.58   158.9  700.94
   168.5  701.27   178.2  701.63   187.9  701.96   197.6  702.35   207.3  703.17
     217  704.79
#Mann= 3 , 0 , 0
       0     .08       0    90.5    .045       0   110.4     .08       0
Bank Sta=90.5,110.4
XS Rating Curve= 0 ,0
Exp/Cntr=0.3,0.1

Type RM Length L Ch R = 1 ,9624.1  ,243.1,241.1,239.2
XS GIS Cut Line= 3
     1768316.891      474955.225     1768390.675      475008.393
     1768505.693       475108.22
#Sta/Elev= 29
       0  699.15     9.1  698.93    18.2  698.71    27.3   698.5    36.4  697.61
    45.5  697.42    54.6  697.63    63.7  697.86    72.8  698.07    81.8  698.19
      91  697.99   100.5  696.84     110  694.32   119.5  690.58   121.2   690.3
     129  689.01   136.2  690.27   138.5  690.67   148.1  696.23   157.6   702.7
   167.1  708.75   176.6  714.84   186.1  720.85   195.6  726.85   205.2   732.7
   214.7  738.45   224.2  743.94   233.7  749.38   243.2  754.83
#Mann= 3 , 0 , 0
       0     .08       0   119.5    .045       0   138.5     .08       0
Bank Sta=119.5,138.5
XS Rating Curve= 0 ,0
Exp/Cntr=0.3,0.1

Type RM Length L Ch R = 1 ,9383    ,236.5,222.2,207.5
XS GIS Cut Line= 4
     1768202.958        475189.6     1768247.446      475204.791
     1768350.528      475279.661     1768424.312      475287.256
#Sta/Elev= 29
       0  718.24     9.4  712.68    18.8  707.05    28.2  701.61    37.6  697.38
      47  695.55    56.8  694.48    66.6  693.37    76.4  691.87    83.5  690.19
    86.2  689.55      96  688.23    98.5  688.96   105.8   691.1   115.6  693.65
   125.4  694.48   135.2   694.5     145  693.98   154.8   694.4   164.6  694.88
   174.4  695.79   183.7  698.64     193   703.6   202.2  709.44   211.5  715.34
   220.8  721.07     230  726.61   239.3  731.77   248.6  736.64
#Mann= 3 , 0 , 0
       0     .08       0    83.5    .045       0    98.5     .08       0
Bank Sta=83.5,98.5
XS Rating Curve= 0 ,0
Exp/Cntr=0.3,0.1

Type RM Length L Ch R = 1 ,9160.8  ,346.6,347.3,347.6
XS GIS Cut Line= 3
     1768155.215       475431.57     1768186.682       475433.74
     1768422.793      475432.221
#Sta/Elev= 26
       0  724.14     7.9  718.79    15.8  712.89    31.5  700.81    41.4  693.35
    51.2  688.02    61.1  686.79    67.1  687.18    70.9  687.42    80.7  688.64
    82.1  688.92    90.6  690.65   100.4  692.13   110.2  692.79   120.1  692.89
   129.9   692.5   139.8   692.8   149.6  693.54   159.4   693.7   198.8   693.6
   208.6  695.36   218.5  699.72   238.1   710.3     248  715.13   257.8  719.38
   267.7  723.19
#Mann= 3 , 0 , 0
       0     .08       0    67.1    .045       0    82.1     .07       0
Bank Sta=67.1,82.1
XS Rating Curve= 0 ,0
Exp/Cntr=0.3,0.1

Type RM Length L Ch R = 1 ,8813.5  ,252.3,264.3,276.4
XS GIS Cut Line= 4
     1768097.706      475782.048     1768182.342      475775.537
     1768325.571      475775.537     1768402.611      475829.791
#Sta/Elev= 21
       0  704.85    18.9  697.94    28.3  695.54    37.7  694.34    75.4  691.99
    94.4  690.89     104   690.4   132.6   689.2   142.2  688.39   151.7  685.81
   161.3  684.06   170.8  686.13   180.4   688.6   189.9  689.41     209  689.73
   218.6  692.71   228.1  698.01     247  708.24   256.4  713.47   284.6  729.57
   322.3  750.42
#Mann= 3 , 0 , 0
       0     .08       0   151.7    .045       0   170.8     .07       0
Bank Sta=151.7,170.8
XS Rating Curve= 0 ,0
Exp/Cntr=0.3,0.1

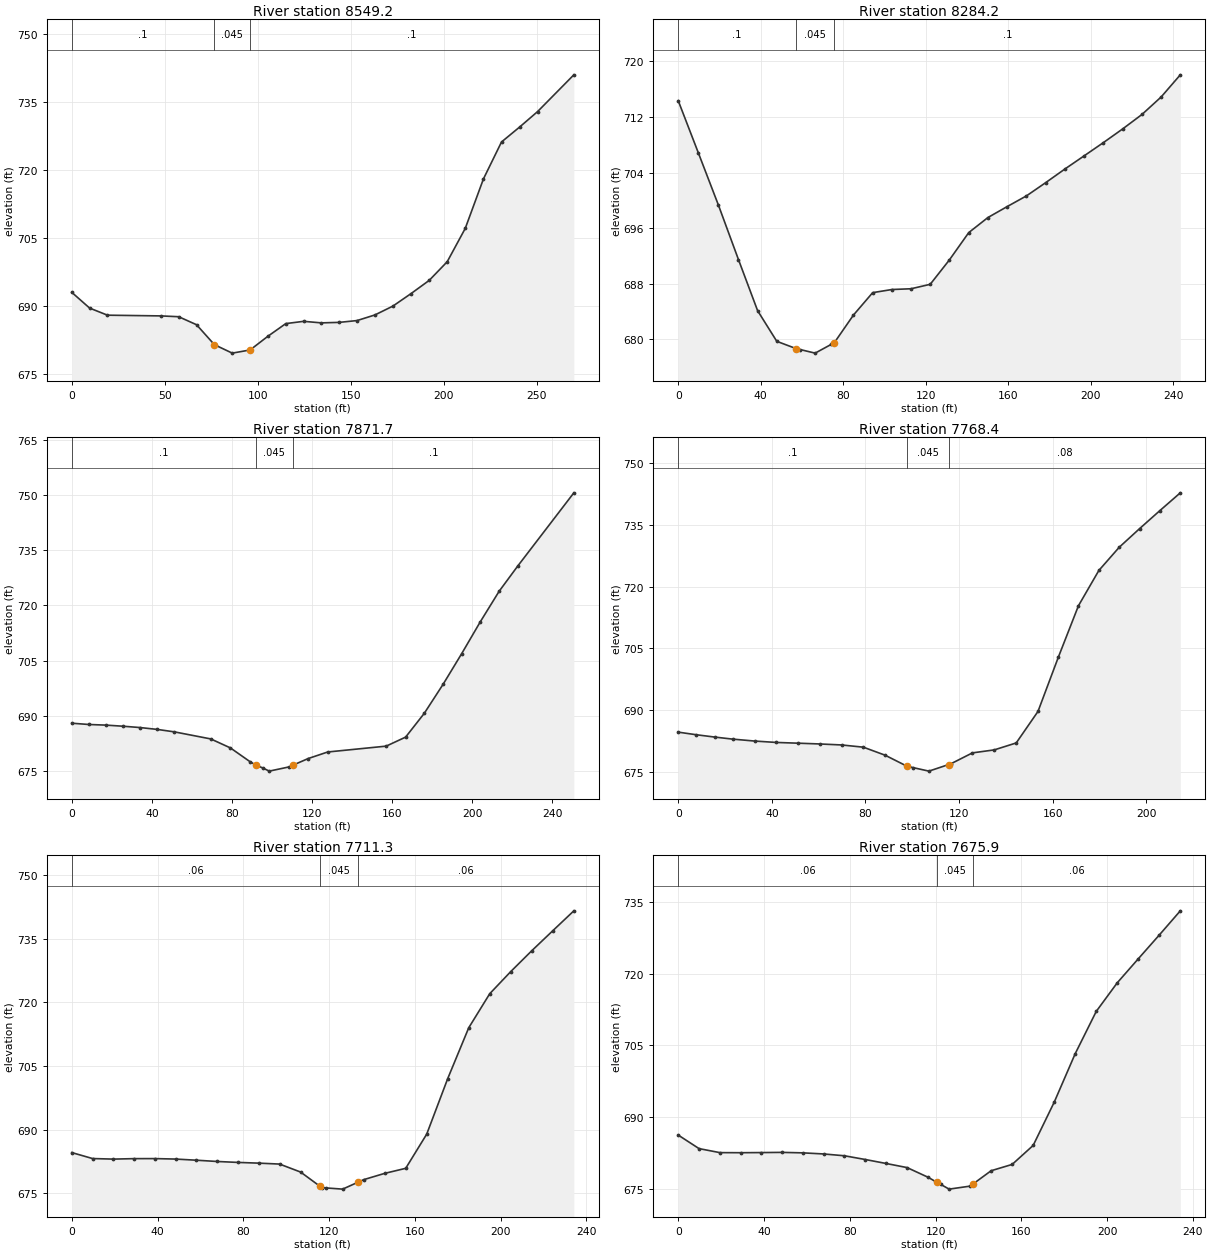
Type RM Length L Ch R = 1 ,8549.2  ,260.6,265,269.2
XS GIS Cut Line= 3
     1768093.366      475974.105      1768233.34      476057.655
      1768314.72        476127.1
#Sta/Elev= 26
       0  692.96     9.6  689.48    19.2  687.91      48  687.75    57.5  687.57
    67.1   685.8    76.7  681.39    86.3  679.52    95.9  680.22   105.5  683.26
   115.1  686.05   124.7  686.55   134.2  686.21   143.8  686.32   153.4  686.72
     163  687.96   172.7  689.92   182.5   692.7   192.2   695.6   201.9  699.73
   211.6   707.1   221.4  718.06   231.1  726.21   240.8   729.5   250.5  732.93
     270  741.06
#Mann= 3 , 0 , 0
       0      .1       0    76.7    .045       0    95.9      .1       0
Bank Sta=76.7,95.9
XS Rating Curve= 0 ,0
Exp/Cntr=0.3,0.1

Type RM Length L Ch R = 1 ,8284.2  ,411.8,412.5,411.9
XS GIS Cut Line= 4
     1767951.222      476177.013     1767972.924      476196.544
     1768042.368      476258.393     1768137.854      476333.263
#Sta/Elev= 29
       0  714.35     9.7  706.88    19.5  699.31    29.2  691.48    38.5  684.11
    47.8   679.7    57.1  678.66    59.2  678.51    66.4     678    74.2  679.26
    75.7   679.5      85  683.49    94.3  686.71   103.6  687.16   112.9  687.27
   122.2  687.91   131.5  691.42   140.9  695.36   150.2  697.53   159.5   699.1
   168.9  700.65   178.2  702.55   187.5  704.51   196.9  706.42   206.2  708.32
   215.5  710.28   224.9  712.37   234.2  714.89   243.5  718.08
#Mann= 3 , 0 , 0
       0      .1       0    57.1    .045       0    75.7      .1       0
Bank Sta=57.1,75.7
XS Rating Curve= 0 ,0
Exp/Cntr=0.3,0.1

Type RM Length L Ch R = 1 ,7871.7  ,97.6,103.3,109.9
XS GIS Cut Line= 4
     1767784.121      476509.044     1767803.653      476565.468
     1767885.033      476634.912     1767933.861      476703.272
#Sta/Elev= 26
       0  687.97     8.5  687.62    17.1  687.45    25.6  687.15    34.1  686.79
    42.6  686.29    51.2  685.62    69.4   683.7    79.2  681.26    88.9  677.56
   91.94  676.58    95.4  675.81    98.6  674.95   108.3  676.07   110.4  676.56
   118.1  678.38   127.8  680.15     157  681.74   166.7  684.19     176  690.64
   185.4  698.53   194.7  706.87     204  715.53   213.4  723.82   222.7  730.68
   250.7  750.56
#Mann= 3 , 0 , 0
       0      .1       0   91.94    .045       0   110.4      .1       0
Bank Sta=91.94,110.4
XS Rating Curve= 0 ,0
Exp/Cntr=0.3,0.1

Type RM Length L Ch R = 1 ,7768.4  ,57.2,57.1,57
XS GIS Cut Line= 4
     1767731.814      476598.353     1767747.439       476615.54
     1767819.314      476724.394     1767846.918      476778.561
#Sta/Elev= 27
       0  684.67     7.7  684.04    15.5  683.48    23.2  682.98    32.6  682.51
    41.9  682.17    51.2  681.99    60.5   681.8    69.8  681.56    79.1  681.02
    88.4  679.07    97.8  676.38   100.5  676.04   107.1  675.21   115.5   676.8
   116.4  676.97   125.7  679.64     135  680.36   144.4  682.05   153.7   689.7
   162.4  702.87     171  715.36   179.7   723.9   188.4  729.53   197.1  734.05
   205.8  738.44   214.5  742.74
#Mann= 3 , 0 , 0
       0      .1       0    97.8    .045       0   115.5     .08       0
Bank Sta=97.8,115.5
XS Rating Curve= 0 ,0
Exp/Cntr=0.3,0.1

Type RM Length L Ch R = 1 ,7711.3  ,35.4,35.4,35.4
XS GIS Cut Line= 3
     1767684.555      476622.065     1767738.809       476702.36
     1767813.679      476817.378
#Sta/Elev= 28
       0  684.62     9.7  683.21    19.4  683.08    29.1  683.19    38.8   683.2
    48.4  683.09    58.1  682.82    67.8  682.52    77.5   682.3    87.2  682.13
    96.9  681.91   106.7  680.03  115.59  676.73   116.5  676.37   118.6  676.29
   126.3  676.01   133.6  677.67   136.1  678.24   145.9  679.72   155.7  680.91
   165.5  688.96   175.3  702.05   185.1  714.02   194.9  722.04   204.7  727.25
   214.5  732.16   224.3  736.87   234.1  741.55
#Mann= 3 , 0 , 0
       0     .06       0  115.59    .045       0   133.6     .06       0
Bank Sta=115.59,133.6
XS Rating Curve= 0 ,0
Exp/Cntr=0.3,0.1

Type RM Length L Ch R = 1 ,7675.9  ,82.7,80.8,78.8
XS GIS Cut Line= 3
     1767654.347      476640.294     1767708.601      476720.589
      1767783.47      476835.607
#Sta/Elev= 28
       0  686.25     9.7  683.42    19.4  682.58    29.1  682.56    38.8  682.59
    48.4  682.63    58.1  682.53    67.8   682.3    77.5  681.92    87.2  681.14
    96.9  680.31   106.7  679.45   116.5  677.42  120.68  676.34   122.4  675.93
   126.3  674.94   136.1  675.57   137.4     676   145.9  678.79   155.7  680.11
   165.5  684.09   175.3  693.13   185.1  703.29   194.9  712.13   204.7  718.12
   214.5  723.14   224.3  728.12   234.1  733.18
#Mann= 3 , 0 , 0
       0     .06       0  120.68    .045       0   137.4     .06       0
Bank Sta=120.68,137.4
XS Rating Curve= 0 ,0
Exp/Cntr=0.3,0.1

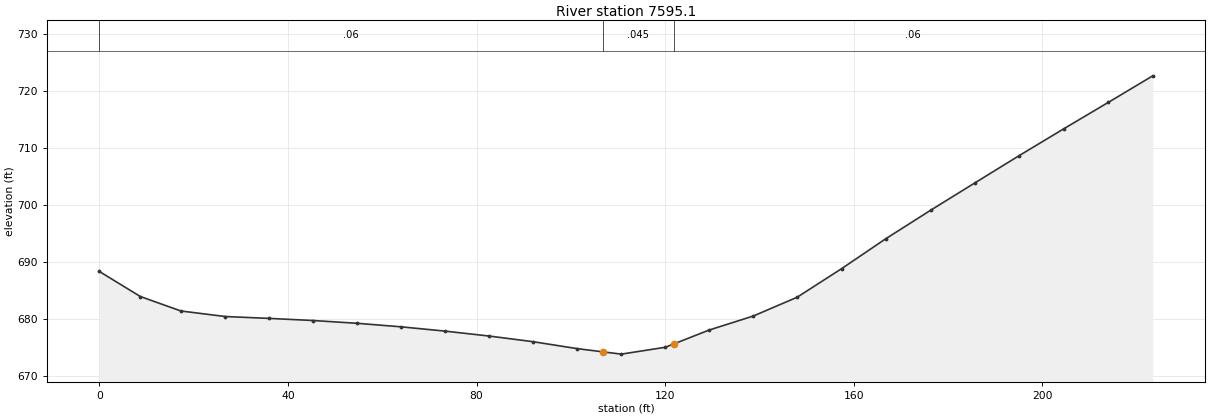
Type RM Length L Ch R = 1 ,7595.1  ,74.5,74.8,75.2
XS GIS Cut Line= 4
     1767588.585      476707.207     1767601.606      476718.665
     1767681.814       476821.79     1767725.564      476883.249
#Sta/Elev= 27
       0  688.27     8.7  683.87    17.3  681.33    26.7  680.36      36  680.03
    45.3  679.66    54.7  679.17      64  678.55    73.3   677.8    82.7  676.93
      92  675.94   101.3  674.73   106.8  674.16   110.7  673.76     120  674.96
   121.8  675.54   129.3  677.98   138.7  680.45     148  683.75   157.4  688.75
   166.8  694.02   176.3  699.01   185.7  703.82   195.1  708.61   204.6  713.34
     214  717.95   223.4   722.6
#Mann= 3 , 0 , 0
       0     .06       0   106.8    .045       0   121.8     .06       0
Bank Sta=106.8,121.8
XS Rating Curve= 0 ,0
Exp/Cntr=0.3,0.1