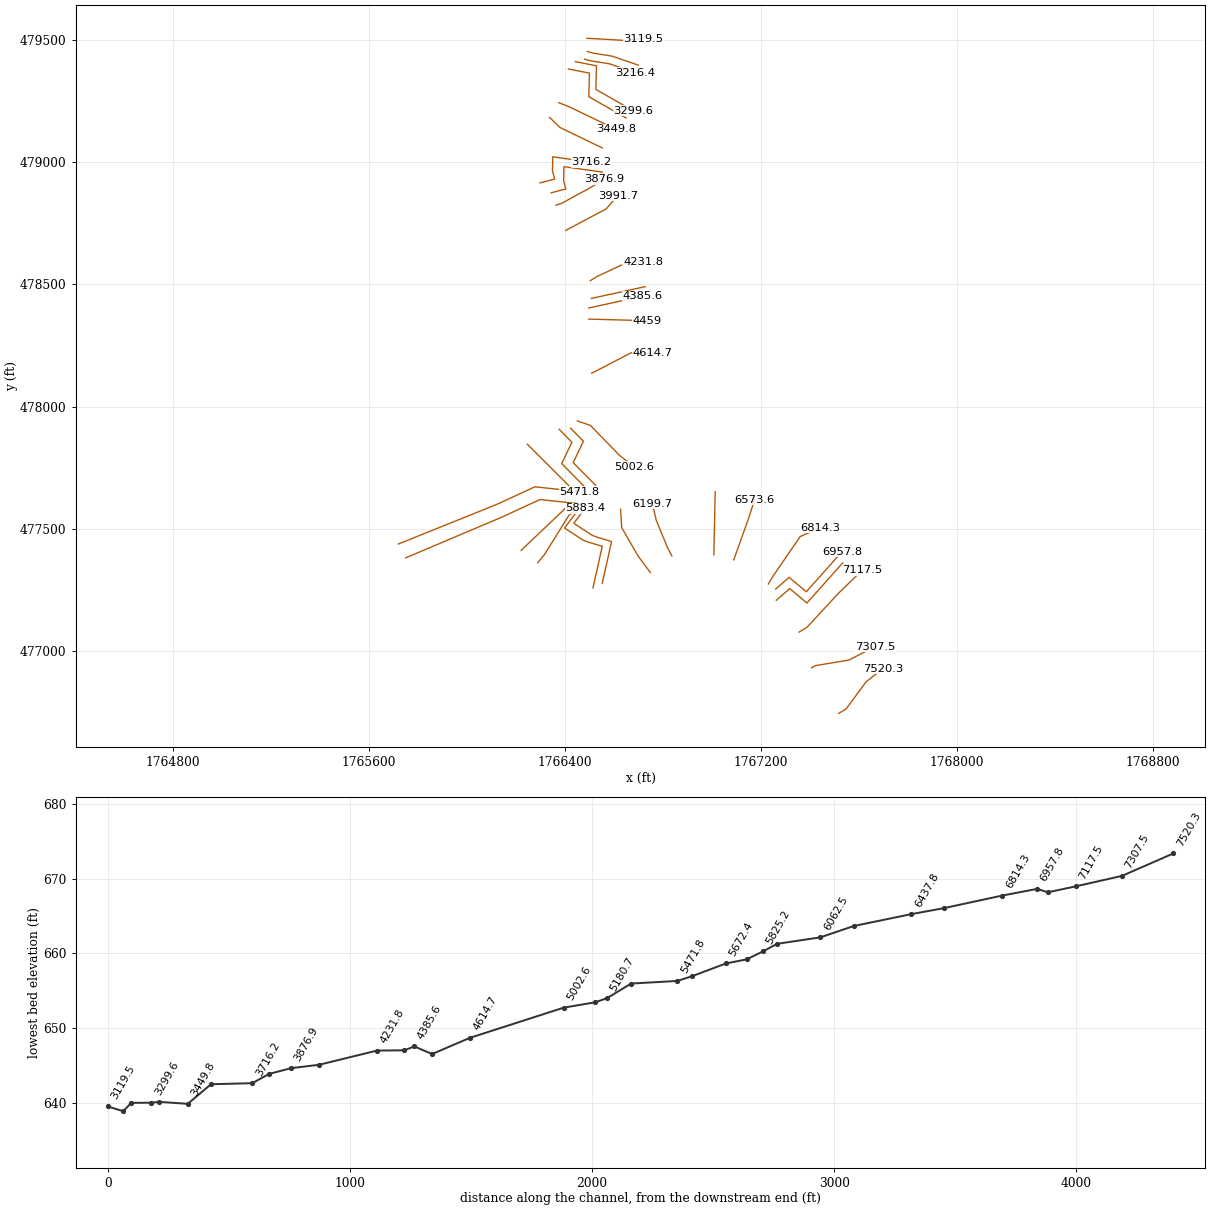
HEC-RAS study MIDFORK1.prj: MIDFORK1

--- MIDFORK1.g01 (geometry) --- (continued)

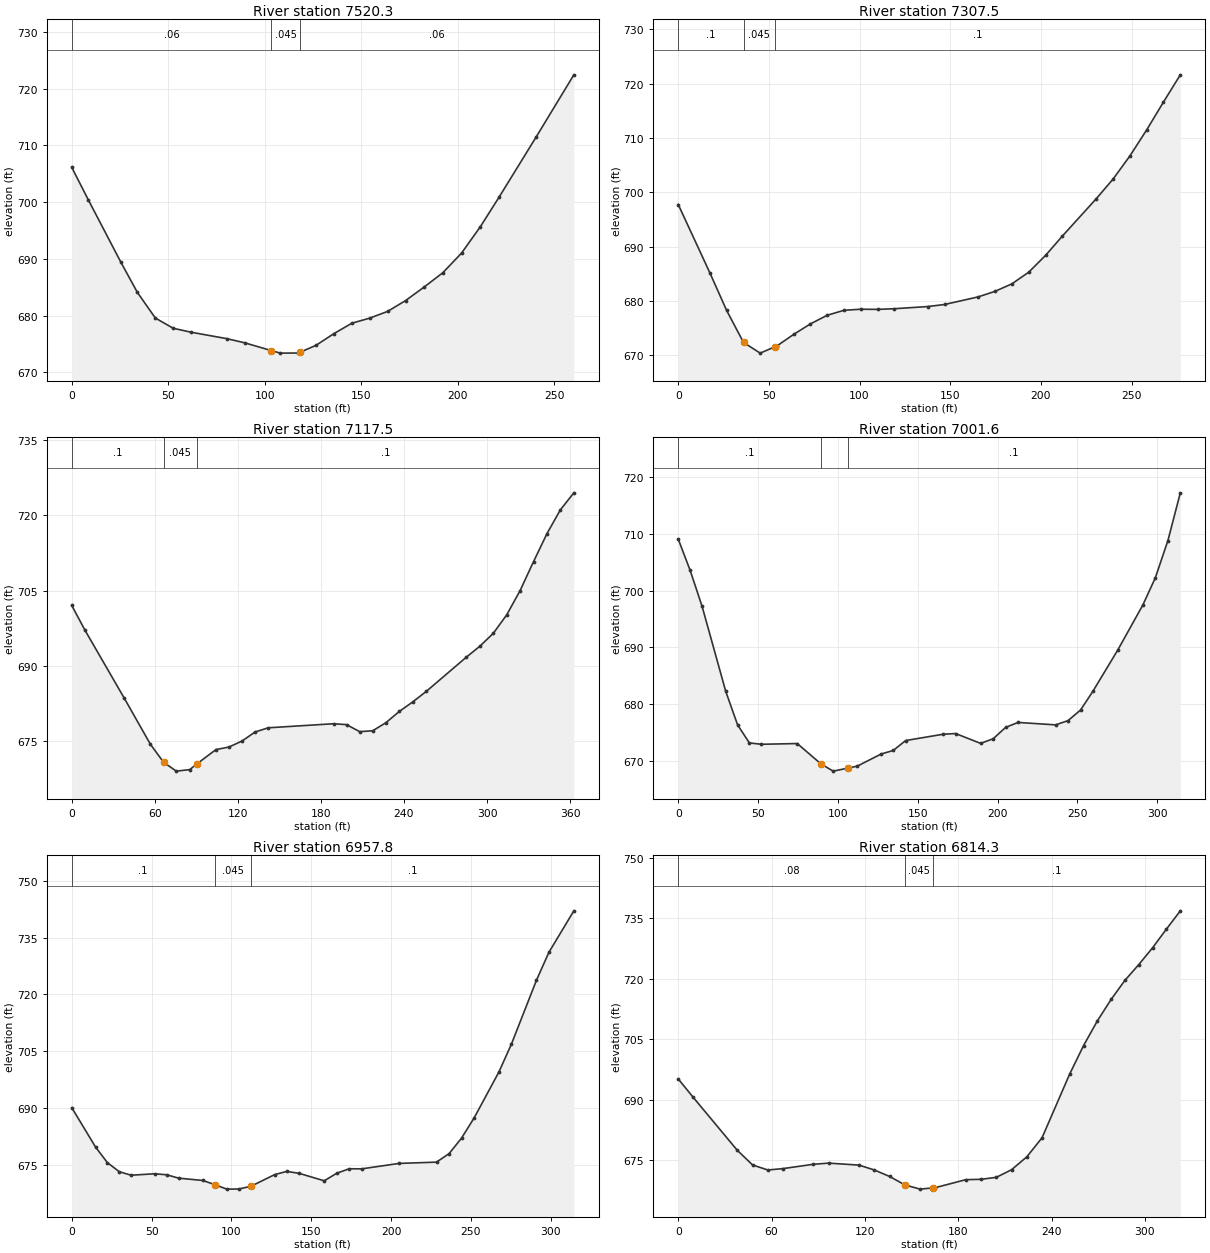
Type RM Length L Ch R = 1 ,7520.3  ,230.1,212.8,195.4
XS GIS Cut Line= 4
     1767517.194      476744.504     1767546.491      476761.865
     1767628.956      476873.628     1767697.316      476927.881
#Sta/Elev= 26
       0  706.14     8.5  700.46    25.5  689.38      34  684.09    43.3  679.57
    52.6  677.76    61.8  677.07    80.4  675.93    89.6   675.2   103.5  673.82
   108.1  673.38   117.4   673.4   118.5  673.56   126.6  674.76   135.9  676.83
   145.2  678.66   154.4  679.55   163.7  680.74     173  682.65   182.6  685.03
   192.3  687.56     202  691.02   211.7  695.65   221.4  700.86   240.8  711.57
   260.2  722.46
#Mann= 3 , 0 , 0
       0     .06       0   103.5    .045       0   118.5     .06       0
Bank Sta=103.5,118.5
XS Rating Curve= 0 ,0
Exp/Cntr=0.3,0.1

Type RM Length L Ch R = 1 ,7307.5  ,174.9,190,205.1
XS GIS Cut Line= 4
     1767406.517      476931.136     1767421.708      476939.817
     1767558.427      476962.603     1767665.849      477017.942
#Sta/Elev= 28
       0  697.75    17.5  685.12    26.7  678.23      36  672.34    45.2  670.37
    53.4  671.55    54.5  671.71    63.7  673.83    72.9  675.76    82.2  677.35
    91.4  678.26   100.7  678.46   109.9  678.43   119.1  678.55   137.6  678.95
   146.9  679.33   165.4  680.73   174.7  681.75     184  683.13   193.3  685.28
   202.6  688.38   211.9  691.95   230.5   698.8   239.8  702.43     249  706.65
   258.4  711.52   267.6  716.62   276.9  721.64
#Mann= 3 , 0 , 0
       0      .1       0      36    .045       0    53.4      .1       0
Bank Sta=36,53.4
XS Rating Curve= 0 ,0
Exp/Cntr=0.3,0.1

Type RM Length L Ch R = 1 ,7117.5  ,154.3,115.9,68.5
XS GIS Cut Line= 4
     1767354.868      477077.187      1767387.42      477096.718
     1767515.458      477235.607     1767613.114      477330.008
#Sta/Elev= 30
       0  702.02     9.5   697.1      38  683.49    56.8  674.34    66.3  670.75
    75.5  668.98    85.2  669.28    90.5  670.44   104.1  673.27   113.5  673.78
     123  674.98   132.4  676.78   141.9  677.62   189.1  678.43   198.5  678.25
     208  676.85   217.4  677.03   226.9  678.63   236.6  680.88   246.3  682.78
     256  684.86   285.1  691.72   294.8  693.89   304.5  696.46   314.2  700.14
   323.9     705   333.6  710.77   343.3  716.35     353   721.1   362.7  724.48
#Mann= 3 , 0 , 0
       0      .1       0    66.3    .045       0    90.5      .1       0
Bank Sta=66.3,90.5
XS Rating Curve= 0 ,0
Exp/Cntr=0.3,0.1

Type RM Length L Ch R = 1 ,7001.6  ,49.1,43.8,52.9
XS GIS Cut Line= 4
     1767262.369       477207.38     1767317.057      477255.124
     1767387.369      477196.096     1767533.203      477360.158
#Sta/Elev= 30
       0  709.06   7.454  703.55  14.909  697.24  29.735  682.25   37.19  676.32
  44.562  673.15  52.016  672.91  74.543  673.04  89.533  669.42   97.07  668.18
 106.326  668.71 112.142  669.06 127.132   671.2 134.669  671.82 142.451  673.57
  165.96  674.68 173.742   674.8 189.388  673.07 197.252  673.88 205.034  675.88
 212.816  676.76 236.325  676.33 244.107  677.07 251.971  678.94 259.753  682.26
 275.399  689.56 291.045  697.47 298.827  702.24 306.691  708.78 314.472  717.21
#Mann= 3 , 0 , 0
       0      .1       0  89.533    .045       0 106.326      .1       0
Bank Sta=89.533,106.326
XS Rating Curve= 0 ,0
Skew Angle= 35
Exp/Cntr=0.3,0.1

Type RM Length L Ch R = 1 ,6957.8  ,93.1,143.5,188.5
XS GIS Cut Line= 4
     1767259.765      477253.387     1767314.453       477301.13
     1767384.765      477242.103     1767530.599      477406.165
#Sta/Elev= 30
       0  690.12  14.909  679.73  22.281  675.64  29.735  673.24   37.19  672.31
  52.016  672.69   59.47  672.42  67.007  671.53  81.997  670.93  89.533  669.84
   97.07  668.64 104.606  668.67 112.142  669.38 127.132  672.48 134.669  673.31
 142.451   672.8 158.096  670.84  165.96  672.82 173.742  674.01 181.606  673.99
 205.034  675.42 228.462  675.76 236.325     678 244.107  682.08 251.971  687.39
 267.535  699.53 275.399  706.91 291.045  723.72 298.827  731.08 314.472  742.04
#Mann= 3 , 0 , 0
       0      .1       0  89.533    .045       0 112.142      .1       0
Bank Sta=89.533,112.142
XS Rating Curve= 0 ,0
Skew Angle= 35
Exp/Cntr=0.3,0.1

Type RM Length L Ch R = 1 ,6814.3  ,238.9,240.7,242.4
XS GIS Cut Line= 4
     1767229.651      477274.018     1767249.182       477306.57
     1767359.859      477468.246     1767441.239      477504.053
#Sta/Elev= 30
       0  695.12     9.5   690.6      38  677.38    47.8  673.75    57.6   672.5
    67.4  672.85    86.9  673.92    96.7  674.21   116.3  673.71   126.1   672.5
   135.9  670.89   145.7   668.8   155.5  667.75   164.1  668.07   165.3  668.12
   184.9   670.1   194.7  670.19   204.5  670.68   214.3  672.57   224.1  675.76
   233.9   680.5   251.7  696.35   260.6   703.4   269.5  709.55   278.4  714.91
   287.2   719.6   296.1  723.51     305   727.7   313.9  732.34   322.8  736.86
#Mann= 3 , 0 , 0
       0     .08       0   145.7    .045       0   164.1      .1       0
Bank Sta=145.7,164.1
XS Rating Curve= 0 ,0
Exp/Cntr=0.3,0.1

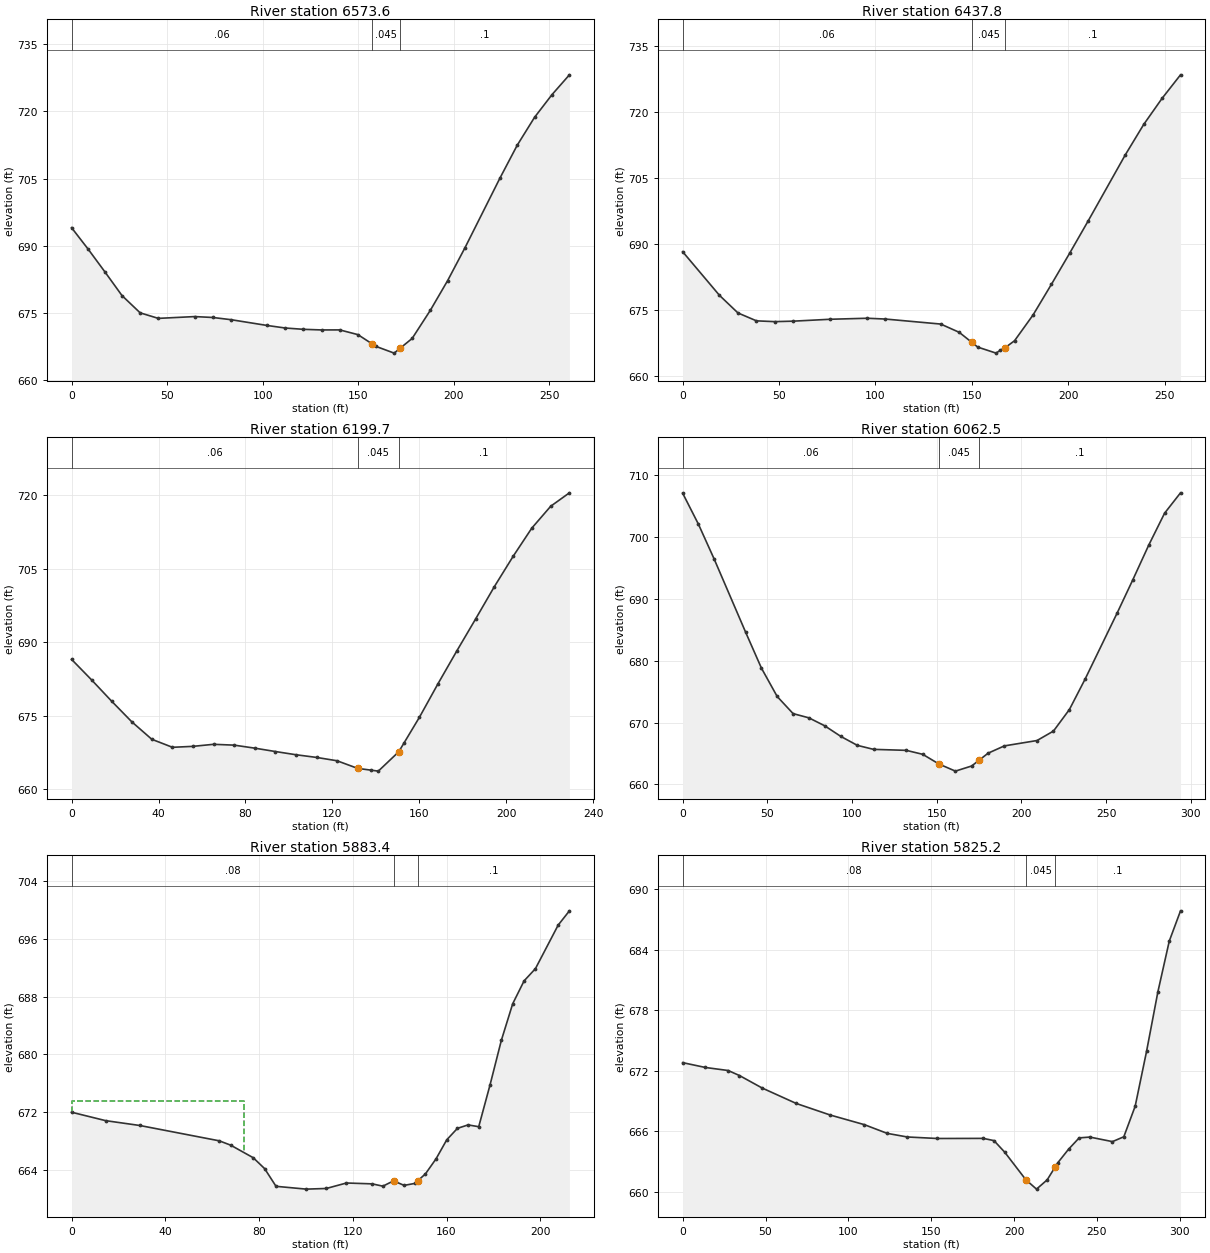
Type RM Length L Ch R = 1 ,6573.6  ,128.4,135.8,143.1
XS GIS Cut Line= 4
     1767088.592       477372.76     1767097.272      477397.716
     1767151.526      477549.626     1767173.227       477619.07
#Sta/Elev= 28
       0  694.05     8.8  689.19    17.6   684.1    26.4   678.9    35.9  675.05
    45.4  673.82    64.4  674.22    73.9  674.02    83.4  673.53   102.3  672.24
   111.8  671.67   121.3  671.38   130.8  671.24   140.3  671.25   149.8   670.2
   157.1  668.18   159.3  667.57   168.8  666.07   172.1  667.22   178.2  669.34
   187.7   675.6   196.8  682.26   205.9  689.61   224.1  705.06   233.2  712.44
   242.3  718.68   251.4  723.72   260.5  728.13
#Mann= 3 , 0 , 0
       0     .06       0   157.1    .045       0   172.1      .1       0
Bank Sta=157.1,172.1
XS Rating Curve= 0 ,0
Exp/Cntr=0.3,0.1

Type RM Length L Ch R = 1 ,6437.8  ,228.4,238,245.8
XS GIS Cut Line= 2
     1767007.212      477393.376     1767012.637      477651.622
#Sta/Elev= 25
       0  688.29    19.1  678.38    28.7  674.38    38.3  672.59    47.8  672.41
    57.4  672.52    76.5  672.95    95.7  673.18   105.2     673   133.9  671.86
   143.5  669.98   149.9  667.75   153.1  666.63   162.6  665.26   164.9  665.94
   167.4  666.52   172.2  668.08   181.8  673.93   191.3  680.87   200.9  688.04
   210.5  695.37   229.6  710.25   239.2  717.19   248.7   723.1   258.3  728.46
#Mann= 3 , 0 , 0
       0     .06       0   149.9    .045       0   167.4      .1       0
Bank Sta=149.9,167.4
XS Rating Curve= 0 ,0
Exp/Cntr=0.3,0.1

Type RM Length L Ch R = 1 ,6199.7  ,134.2,137.2,141.3
XS GIS Cut Line= 4
     1766835.771      477389.036      1766818.41      477421.588
     1766771.752       477535.52     1766756.561      477602.794
#Sta/Elev= 28
       0  686.51     9.2  682.32    18.4  677.98    27.7  673.75    36.9  670.18
    46.4  668.54    55.8  668.73    65.3  669.15    74.8  668.98    84.2  668.37
    93.7  667.68   103.2  667.02   112.7  666.47   122.1  665.79   131.6  664.23
   137.9  663.86   141.1  663.67   150.5  667.63   152.9  669.41     160  674.67
   168.6  681.57   177.2  688.23   185.9   694.8   194.5  701.39   203.1  707.56
   211.7  713.33   220.4   717.8     229  720.54
#Mann= 3 , 0 , 0
       0     .06       0   131.6    .045       0   150.5      .1       0
Bank Sta=131.6,150.5
XS Rating Curve= 0 ,0
Exp/Cntr=0.3,0.1

Type RM Length L Ch R = 1 ,6062.5  ,83.9,179.1,200.8
XS GIS Cut Line= 4
      1766747.88      477320.676     1766697.967      477387.951
     1766630.693      477505.138     1766626.352      477580.008
#Sta/Elev= 29
       0  707.11     9.3   702.1    18.6  696.46    37.2  684.61    46.5  678.82
    55.8  674.23    65.2  671.46    74.5  670.78    83.8   669.5    93.4  667.77
   103.1  666.33   112.7  665.68     132  665.52   141.7  664.88   151.3  663.31
     161  662.16   170.6  662.99   175.1  663.95   180.3  665.06   189.9  666.24
   209.2  667.11   218.9  668.64   228.3  672.12   237.6  677.06   256.4  687.68
   265.8  693.14   275.1  698.69   284.5  703.88   293.9  707.17
#Mann= 3 , 0 , 0
       0     .06       0   151.3    .045       0   175.1      .1       0
Bank Sta=151.3,175.1
XS Rating Curve= 0 ,0
Exp/Cntr=0.3,0.1

Type RM Length L Ch R = 1 ,5883.4  ,138.9,58.2,50.9
XS GIS Cut Line= 6
     1766551.483      477277.273      1766589.46      477447.629
     1766531.951       477464.99     1766511.335      477472.586
      1766435.38      477522.499     1766482.038      477584.348
#Sta/Elev= 30
       0  671.96   14.55  670.79    29.1  670.12   63.05  667.99    67.9  667.39
   77.55  665.64    82.4  664.13   87.25  661.68  100.15  661.29   108.7  661.38
   117.3  662.14   128.3  662.02  132.85   661.7   137.4  662.44   141.9  661.81
  146.45  662.08   147.8  662.47     151   663.4  155.55   665.5   160.1  668.13
  164.65  669.72   169.2   670.2  173.75  669.95   178.6  675.78   183.4  681.93
  188.25  687.01   193.1  690.18  197.95  691.88  207.65  697.92  212.45   699.9
#Mann= 3 , 0 , 0
       0     .08       0   137.4    .045       0   147.8      .1       0
#XS Ineff= 2 , 0
           73.72  673.48
Permanent Ineff=
       F       F
Bank Sta=137.4,147.8
XS Rating Curve= 0 ,0
Skew Angle= 60
Exp/Cntr=0.3,0.1

Type RM Length L Ch R = 1 ,5825.2  ,109.8,67.8,25.9
XS GIS Cut Line= 6
     1766513.505      477257.742     1766551.483      477428.098
     1766493.974      477445.459     1766473.358      477453.055
     1766397.403      477502.968     1766444.061      477564.817
#Sta/Elev= 29
       0  672.82  13.718  672.34  27.436  672.04  34.295  671.54  48.013   670.3
  68.589  668.77  89.166  667.62 109.672  666.67  123.39  665.81 135.552  665.45
 153.725   665.3 181.444  665.31 187.878  665.09 194.313  663.95 207.112  661.21
 213.546  660.28 219.981   661.2 224.931  662.51 226.416   662.9  232.85  664.23
 239.285  665.36  245.72  665.44 259.367  664.99 266.226  665.47 273.085   668.5
 279.944  673.93 286.803  679.85 293.661  684.87  300.45  687.87
#Mann= 3 , 0 , 0
       0     .08       0 207.112    .045       0 224.931      .1       0
Bank Sta=207.112,224.931
XS Rating Curve= 0 ,0
Skew Angle= 45
Exp/Cntr=0.3,0.1

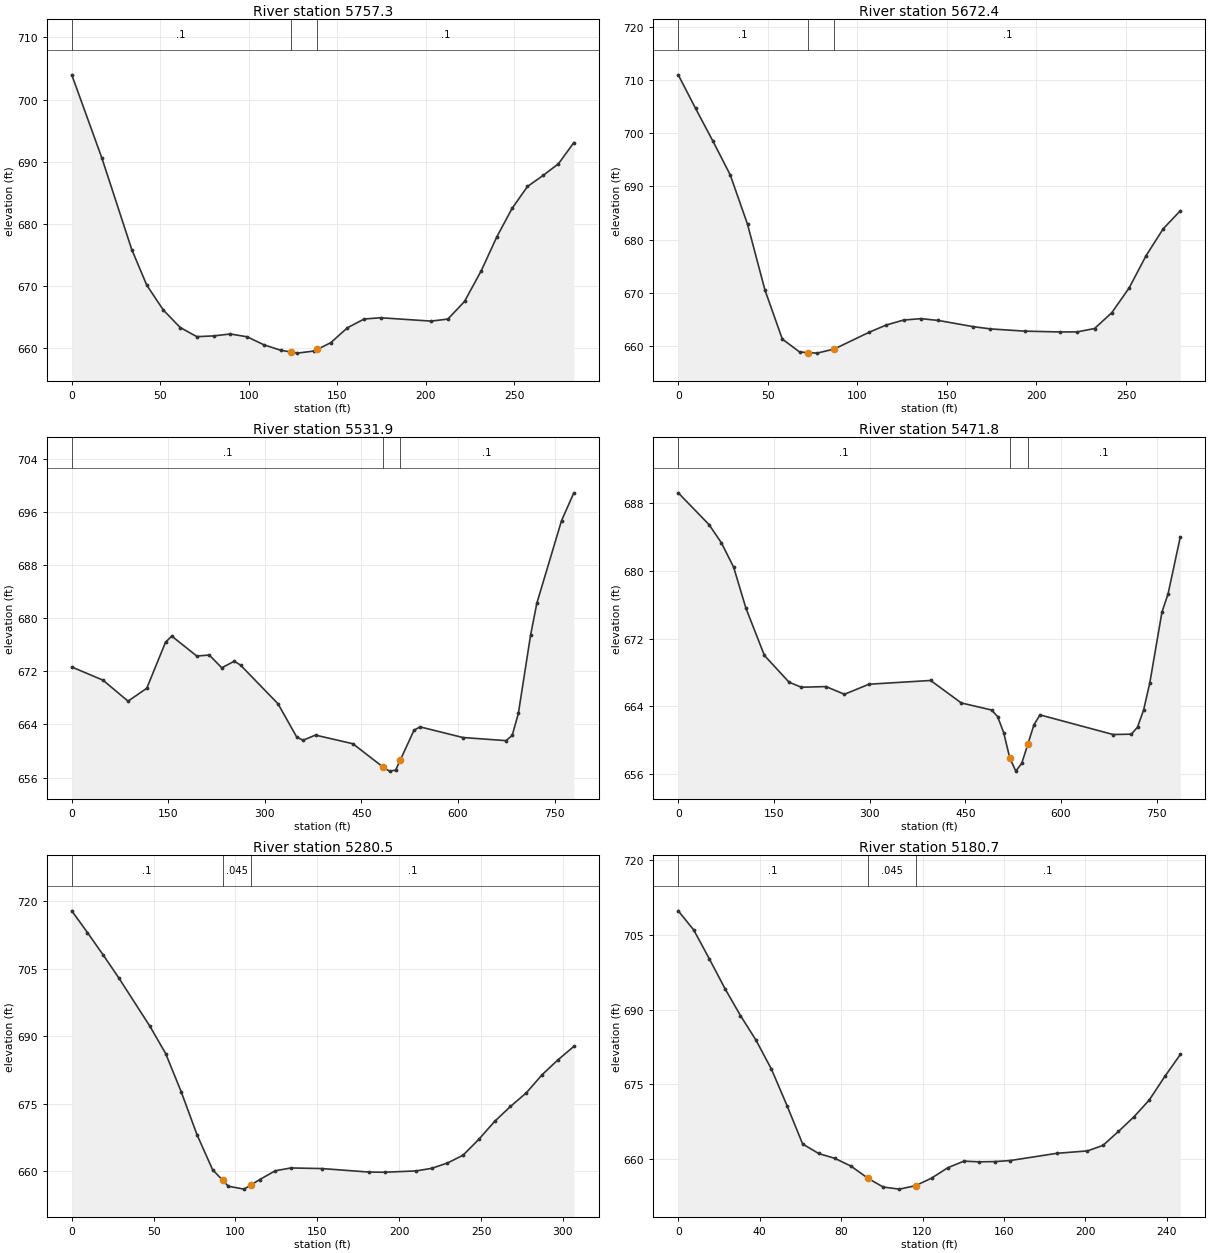
Type RM Length L Ch R = 1 ,5757.3  ,88.3,84.9,79.5
XS GIS Cut Line= 4
     1766287.811      477360.824     1766314.937      477393.376
     1766414.764      477553.966     1766454.911      477587.603
#Sta/Elev= 30
       0  703.98      17  690.61    33.9  675.88    42.4  670.14    51.8  666.13
    61.3  663.33    70.7  661.86    80.2  661.98    89.6  662.29    99.1  661.84
   108.6  660.55     118  659.68   123.7   659.4   127.5  659.21   136.9  659.55
   138.7   659.8   146.4  660.89   155.8  663.29   165.3   664.7   174.7   664.9
   203.1  664.36   212.6  664.69     222  667.52   231.5  672.49   240.2  677.88
   248.9   682.5   257.6  686.02   266.4  687.79   275.1  689.67   283.8  693.08
#Mann= 3 , 0 , 0
       0      .1       0   123.7    .045       0   138.7      .1       0
Bank Sta=123.7,138.7
XS Rating Curve= 0 ,0
Exp/Cntr=0.3,0.1

Type RM Length L Ch R = 1 ,5672.4  ,147.1,140.5,136
XS GIS Cut Line= 3
     1766220.102      477411.388     1766402.394      477584.999
     1766430.606      477589.339
#Sta/Elev= 27
       0  710.96     9.7  704.64    19.4  698.48      29  692.18    38.7  682.86
    48.4  670.53    58.1  661.31    67.8  658.88    72.3  658.78    77.5  658.67
    87.1  659.44   106.5  662.58   116.2  663.96   125.9  664.89   135.6  665.15
   145.2  664.81   164.6  663.65   174.3  663.22   193.6   662.8     213  662.65
   222.7  662.66   232.4  663.29     242  666.25   251.7   670.9   261.2  676.99
   270.8  682.06   280.3  685.42
#Mann= 3 , 0 , 0
       0      .1       0    72.3    .045       0    87.1      .1       0
Bank Sta=72.3,87.1
XS Rating Curve= 0 ,0
Exp/Cntr=0.3,0.1

Type RM Length L Ch R = 1 ,5531.9  ,60,60.1,60.3
XS GIS Cut Line= 4
     1765749.182      477381.006     1766142.411       477547.89
     1766297.359      477619.504     1766478.349      477599.973
#Sta/Elev= 30
       0  672.63    48.5  670.65    87.4  667.49   116.5  669.43   145.6  676.35
   155.3  677.28   194.2  674.28   213.6  674.43     233  672.51   252.4   673.5
   262.1  672.92   320.4  667.09   349.5  662.08   359.2  661.61   378.6  662.38
   436.7  661.08   484.1  657.53   493.6  656.96     503  657.11   510.1  658.57
   531.5   663.1     541  663.62   607.4  662.02   674.5  661.55   684.1  662.33
   693.7  665.64   712.8  677.48   722.4  682.22   760.8  694.66   779.9  698.84
#Mann= 3 , 0 , 0
       0      .1       0   484.1    .045       0   510.1      .1       0
Bank Sta=484.1,510.1
XS Rating Curve= 0 ,0
Exp/Cntr=0.3,0.1

Type RM Length L Ch R = 1 ,5471.8  ,218.9,191.3,162.9
XS GIS Cut Line= 4
       1765718.8       477437.43     1766121.578      477599.973
     1766276.526      477671.588     1766457.516      477652.056
#Sta/Elev= 30
       0  689.24    48.3  685.48    67.6  683.34    86.9  680.44   106.2  675.58
   135.1  670.01   173.7  666.85     193  666.25   231.6  666.33   260.6  665.42
   299.2  666.61   395.7  667.05   443.8  664.39   491.2  663.56   500.7  662.78
   510.2  660.88   519.7   657.9   529.2  656.33   538.6  657.28   548.1  659.52
   557.6   661.8   567.1  662.98   681.7  660.66   710.4   660.7     720  661.53
   729.6  663.57   739.2  666.74   758.3  675.13   767.9  677.29   787.1  684.04
#Mann= 3 , 0 , 0
       0      .1       0   519.7    .045       0   548.1      .1       0
Bank Sta=519.7,548.1
XS Rating Curve= 0 ,0
Exp/Cntr=0.3,0.1

Type RM Length L Ch R = 1 ,5280.5  ,130.1,99.7,70.1
XS GIS Cut Line= 3
     1766245.276      477846.067     1766421.057      477670.286
     1766477.047      477654.661
#Sta/Elev= 30
       0  717.87     9.6  713.03    19.1   708.1    28.7  702.97    47.8  692.16
    57.4   686.1    66.9  677.58    76.5  668.09      86  660.32    92.1  657.98
    95.6  656.63   105.2  655.98  109.74  656.96   114.7  658.09   124.3  660.06
   133.9  660.69     153  660.55   181.7  659.77   191.2  659.74   210.4  660.03
   219.9  660.61   229.5  661.79     239  663.52   248.6  667.03   258.3  671.04
     268  674.37   277.7  677.41   287.3  681.42     297  684.73   306.7  687.72
#Mann= 3 , 0 , 0
       0      .1       0    92.1    .045       0  109.74      .1       0
Bank Sta=92.1,109.74
XS Rating Curve= 0 ,0
Exp/Cntr=0.3,0.1

Type RM Length L Ch R = 1 ,5180.7  ,47.6,49.2,49.5
XS GIS Cut Line= 4
     1766375.484      477907.265     1766427.568      477853.879
     1766385.901       477766.64     1766477.047      477674.192
#Sta/Elev= 30
       0  709.79   7.618  705.95  15.236   700.2  22.936  694.22  30.554  688.81
  38.172  683.89  45.791  678.06  53.491  670.71  61.109  663.07  68.973  661.16
  76.918  660.19  84.864  658.63  93.301  656.17 100.674  654.44  108.62  654.02
 116.565  654.71 124.429  656.22 132.375   658.3 140.321  659.63 147.857  659.49
 155.475  659.54 163.093  659.75 185.866  661.19  201.02  661.68 208.638  662.78
 216.256  665.58 223.874  668.51  231.41  671.89 239.029   676.6 246.647     681
#Mann= 3 , 0 , 0
       0      .1       0  93.301    .045       0 116.565      .1       0
Bank Sta=93.301,116.565
XS Rating Curve= 0 ,0
Skew Angle= 35
Exp/Cntr=0.3,0.1

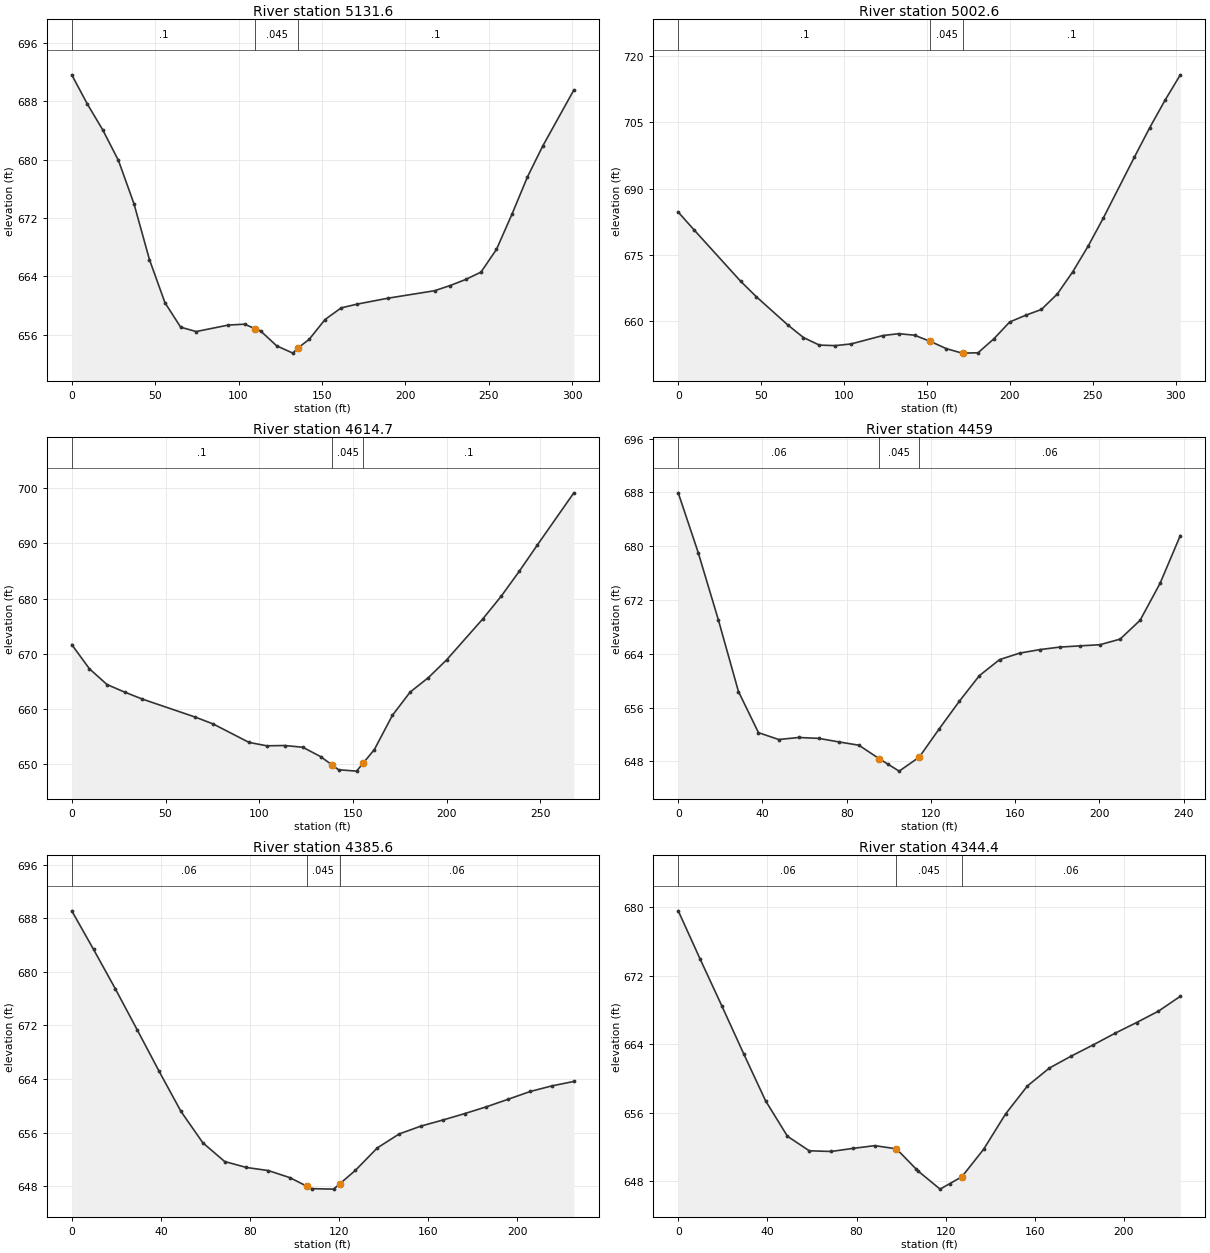
Type RM Length L Ch R = 1 ,5131.6  ,100.4,129,157.9
XS GIS Cut Line= 4
     1766422.359      477911.171     1766474.443      477857.786
     1766432.776      477770.546     1766523.922      477678.098
#Sta/Elev= 30
       0  691.64     9.3  687.65    18.6  684.08      28  679.89    37.3  673.96
    46.6  666.29    55.9  660.38    65.3  657.03    74.6  656.43    93.9  657.32
   103.6  657.44   110.1  656.81   113.3   656.5   122.9  654.47   132.6  653.47
  135.47  654.15   142.3  655.34   151.9  658.08   161.6  659.68   171.3   660.2
   189.8  661.01   217.6  662.03   226.9  662.74   236.2  663.57   245.4  664.58
   254.7   667.7     264  672.53   273.3  677.65   282.5   681.9   301.1  689.56
#Mann= 3 , 0 , 0
       0      .1       0   110.1    .045       0  135.47      .1       0
Bank Sta=110.1,135.47
XS Rating Curve= 0 ,0
Exp/Cntr=0.3,0.1

Type RM Length L Ch R = 1 ,5002.6  ,359,388,416.9
XS GIS Cut Line= 4
     1766449.703      477941.119     1766503.088       477922.89
      1766622.88      477799.192     1766681.474      477753.619
#Sta/Elev= 29
       0  684.69     9.4  680.72    37.6  669.05      47  665.56      66  659.17
    75.5  656.29    85.1  654.58    94.7  654.46   104.2  654.84   123.4  656.74
   132.9  657.16   142.5  656.82   152.1  655.41   161.6  653.79   171.2  652.76
   171.7  652.76   180.8  652.84   190.3  655.98   199.9  659.81   209.5  661.33
     219  662.64   228.6  666.14   237.9  671.16   247.2  676.98   256.4  683.37
     275  697.05   284.3  703.76   293.6  710.02   302.8  715.76
#Mann= 3 , 0 , 0
       0      .1       0   152.1    .045       0   171.7      .1       0
Bank Sta=152.1,171.7
XS Rating Curve= 0 ,0
Exp/Cntr=0.3,0.1

Type RM Length L Ch R = 1 ,4614.7  ,167.1,155.6,144
XS GIS Cut Line= 4
     1766508.297      478136.431     1766566.891      478166.379
     1766668.453      478219.765     1766755.693      478217.161
#Sta/Elev= 26
       0  671.65     9.4  667.27    18.8  664.41    28.2  663.04    37.6  661.78
    65.8  658.52    75.4  657.27    94.5  653.93     104  653.31   113.6  653.36
   123.2  653.05   132.7  651.36   138.7  649.87   142.3  648.97   151.9  648.72
  155.45  650.18   161.4  652.63     171  658.82   180.5  663.05   190.2  665.66
   199.9  668.87   219.3  676.33     229  680.39   238.7  684.94   248.4  689.73
   267.8  699.15
#Mann= 3 , 0 , 0
       0      .1       0   138.7    .045       0  155.45      .1       0
Bank Sta=138.7,155.45
XS Rating Curve= 0 ,0
Exp/Cntr=0.3,0.1

Type RM Length L Ch R = 1 ,4459    ,66.4,73.4,79.6
XS GIS Cut Line= 2
     1766496.578      478357.786     1766734.859      478351.275
#Sta/Elev= 28
       0  687.93     9.5  679.03    19.1     669    28.6  658.39    38.1  652.28
    47.7  651.26    57.2  651.56    66.7  651.43    76.3   650.9    85.8  650.41
    95.4  648.41    99.7  647.57   104.9  646.56   114.4  648.63   114.7  648.76
     124  652.88   133.5  656.96     143  660.76   152.6  663.14   162.1   664.1
   171.6  664.62   181.2     665   190.7  665.18   200.2  665.35   209.8  666.18
   219.3  668.98   228.8  674.49   238.4  681.58
#Mann= 3 , 0 , 0
       0     .06       0    95.4    .045       0   114.4     .06       0
Bank Sta=95.4,114.4
XS Rating Curve= 0 ,0
Exp/Cntr=0.3,0.1

Type RM Length L Ch R = 1 ,4385.6  ,41.6,41.2,41.8
XS GIS Cut Line= 2
     1766496.578      478403.358      1766716.63      478451.536
#Sta/Elev= 26
       0   689.1     9.8  683.33    19.6  677.43    29.4  671.32    39.2  665.15
      49  659.17    58.8  654.49    68.6  651.69    78.4   650.8    88.2  650.34
    97.9  649.28   105.4  648.02   107.7  647.64   117.5  647.57   120.4   648.4
   127.3  650.38   137.1  653.72   146.9   655.8   156.7  656.98   166.5  657.88
   176.3  658.84   186.1  659.86   195.9  660.99   205.7  662.14   215.5  662.98
   225.3  663.64
#Mann= 3 , 0 , 0
       0     .06       0   105.4    .045       0   120.4     .06       0
Bank Sta=105.4,120.4
XS Rating Curve= 0 ,0
Exp/Cntr=0.3,0.1

Type RM Length L Ch R = 1 ,4344.4  ,108.2,112.7,116.2
XS GIS Cut Line= 2
     1766506.995      478442.421     1766727.047      478490.598
#Sta/Elev= 26
       0  679.58     9.8  673.96    19.6  668.45    29.4  662.86    39.2  657.38
      49  653.24    58.8  651.54    68.6  651.46    78.4  651.82    88.2  652.14
    97.9  651.77   106.9  649.37   107.7  649.16   117.5  647.06   121.9  647.71
   127.3  648.51   137.1  651.74   146.9  655.85   156.7  659.12   166.5   661.2
   176.3   662.6   186.1   663.9   195.9  665.26   205.7  666.53   215.5  667.86
   225.3  669.59
#Mann= 3 , 0 , 0
       0     .06       0    97.9    .045       0   127.3     .06       0
Bank Sta=97.9,127.3
XS Rating Curve= 0 ,0
Exp/Cntr=0.3,0.1

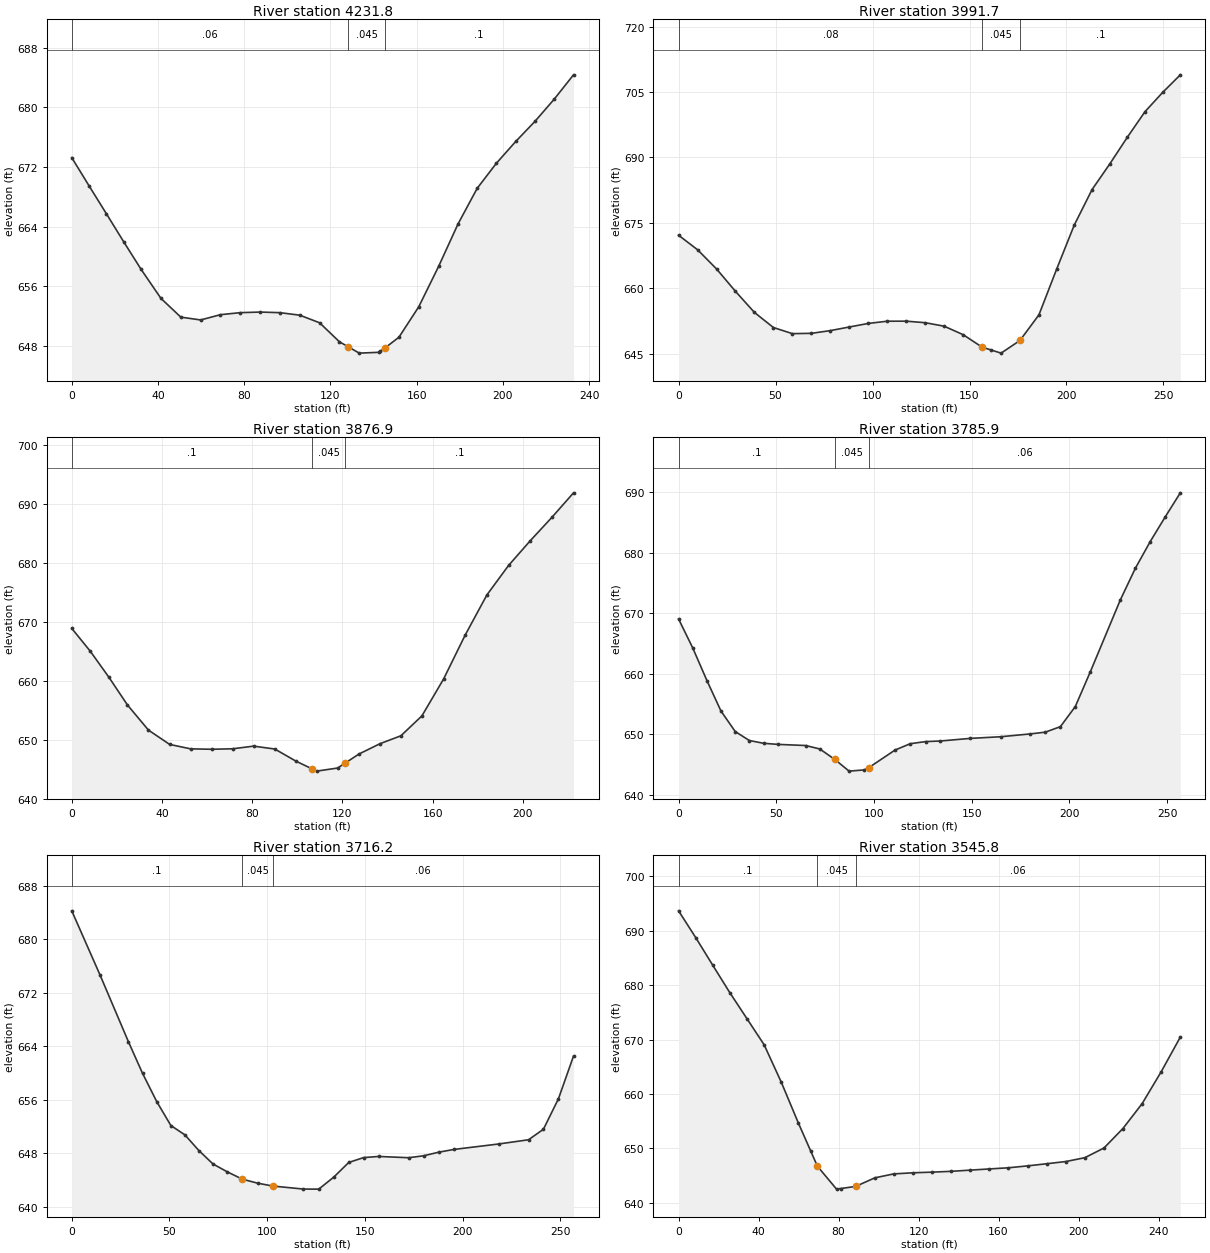
Type RM Length L Ch R = 1 ,4231.8  ,239.5,240,243.5
XS GIS Cut Line= 4
     1766503.088      478515.338     1766530.432      478532.265
     1766655.432      478590.858     1766717.932      478593.463
#Sta/Elev= 30
       0  673.25       8  669.48    16.1  665.71    24.1  661.96    32.2  658.25
    41.4  654.36    50.6  651.85    59.8  651.47      69  652.18    78.2  652.45
    87.4  652.53    96.6  652.45   105.8  652.11     115  651.09   124.2  648.54
   128.2  647.88   133.4  647.02   142.6  647.13   143.2  647.26  145.26   647.7
   151.8  649.15     161  653.24   170.2  658.65   179.2  664.34   188.1  669.13
     197  672.49     206  675.42   214.9  678.11   223.8  681.08   232.8  684.36
#Mann= 3 , 0 , 0
       0     .06       0   128.2    .045       0  145.26      .1       0
Bank Sta=128.2,145.26
XS Rating Curve= 0 ,0
Exp/Cntr=0.3,0.1

Type RM Length L Ch R = 1 ,3991.7  ,115,114.8,113
XS GIS Cut Line= 3
     1766402.828      478721.067     1766566.891      478808.306
     1766615.068      478862.994
#Sta/Elev= 30
       0  672.16     9.8  668.83    19.6  664.42    29.3  659.31    39.1  654.46
    48.9  650.99    58.7  649.59    68.5  649.66    78.2  650.28      88  651.11
    97.8  651.93   107.6  652.44   117.4  652.45   127.1   652.1   136.9   651.3
   146.7  649.36   156.5  646.49   161.2  645.83   166.3  645.12     176  648.02
   176.2  648.14   185.8   653.9   194.9  664.35     204  674.48   213.2  682.64
   222.3  688.49   231.4  694.65   240.5  700.51   249.6  704.92   258.7  708.95
#Mann= 3 , 0 , 0
       0     .08       0   156.5    .045       0   176.2      .1       0
Bank Sta=156.5,176.2
XS Rating Curve= 0 ,0
Exp/Cntr=0.3,0.1

Type RM Length L Ch R = 1 ,3876.9  ,52.3,91,116.5
XS GIS Cut Line= 4
     1766362.463      478823.931     1766385.901      478831.744
     1766500.484      478894.244     1766557.776        478929.4
#Sta/Elev= 27
       0  668.89     8.2  665.02    16.5  660.58    24.7  655.89      34  651.63
    43.4   649.2    52.7  648.45      62  648.38    71.3  648.46    80.6  648.91
      90  648.42    99.3  646.38   106.3  645.09   108.6  644.67   117.9   645.2
   121.3  646.06   127.3  647.57   136.6  649.32   145.9  650.67   155.2  654.04
   164.8  660.29   174.4  667.77     184  674.56   193.6  679.56   203.2  683.75
   212.8  687.72   222.4  691.89
#Mann= 3 , 0 , 0
       0      .1       0   106.3    .045       0   121.3      .1       0
Bank Sta=106.3,121.3
XS Rating Curve= 0 ,0
Exp/Cntr=0.3,0.1

Type RM Length L Ch R = 1 ,3785.9  ,58,69.7,70.7
XS GIS Cut Line= 5
     1766342.932      478874.713     1766402.828      478890.338
     1766393.713      478924.192     1766395.016      478981.483
     1766552.568      478959.348
#Sta/Elev= 30
       0  669.04   7.209  664.28  14.499  658.87  21.708  653.82  28.998  650.44
  36.207  648.96  43.497   648.5  50.706  648.32  65.041  648.13  72.249  647.56
  79.867  645.85   87.24   643.9  95.104   644.1  97.258  644.46 110.749  647.38
 118.531  648.43 126.395  648.78 134.013  648.88 149.331  649.31 164.731  649.58
  180.05  650.05 187.668  650.34 195.368  651.25 202.986  654.57 210.686  660.32
 226.004  672.17 233.704  677.41 241.322  681.83 249.022  685.92 256.722  689.88
#Mann= 3 , 0 , 0
       0      .1       0  79.867    .045       0  97.258     .06       0
Bank Sta=79.867,97.258
XS Rating Curve= 0 ,0
Skew Angle= 35
Exp/Cntr=0.3,0.1

Type RM Length L Ch R = 1 ,3716.2  ,244.4,170.4,122.2
XS GIS Cut Line= 5
     1766297.359      478915.077     1766357.255      478930.702
     1766348.141      478964.556     1766349.443      479021.848
     1766506.995      478999.713
#Sta/Elev= 28
       0  684.22  14.499  674.62  28.998  664.67  36.207  659.96  43.497  655.72
  50.706  652.16  57.914  650.76  65.041  648.42  72.249  646.42  79.458  645.26
   87.24  644.15  95.104  643.55 102.885  643.12 118.531  642.67 126.395  642.66
 134.013  644.44 141.713  646.64 149.331  647.37 157.031  647.54  172.35  647.35
  180.05  647.64 187.668  648.17 195.368  648.58 218.386   649.4 233.704  650.03
 241.322   651.6 249.022  656.16 256.722  662.53
#Mann= 3 , 0 , 0
       0      .1       0   87.24    .045       0 102.885     .06       0
Bank Sta=87.24,102.885
XS Rating Curve= 0 ,0
Skew Angle= 35
Exp/Cntr=0.3,0.1

Type RM Length L Ch R = 1 ,3545.8  ,93,95.9,95.8
XS GIS Cut Line= 3
     1766336.422      479183.306     1766379.391       479141.64
     1766551.266      479058.306
#Sta/Elev= 30
       0  693.66     8.6  688.73    17.1  683.66    25.6  678.64    34.2  673.84
    42.8  669.04    51.3  662.22    59.8  654.76    66.1   649.5    69.4  646.74
      79  642.52    81.1  642.63    88.5  643.01    98.1  644.59   107.6  645.32
   117.2  645.52   126.7  645.64   136.3  645.79   145.8  646.01   155.4  646.23
   164.9  646.44   174.5  646.79     184  647.18   193.6  647.59   203.1  648.29
   212.7  650.07   222.2  653.66   231.8  658.23   241.3  664.07   250.9  670.46
#Mann= 3 , 0 , 0
       0      .1       0    69.4    .045       0    88.5     .06       0
Bank Sta=69.4,88.5
XS Rating Curve= 0 ,0
Exp/Cntr=0.3,0.1

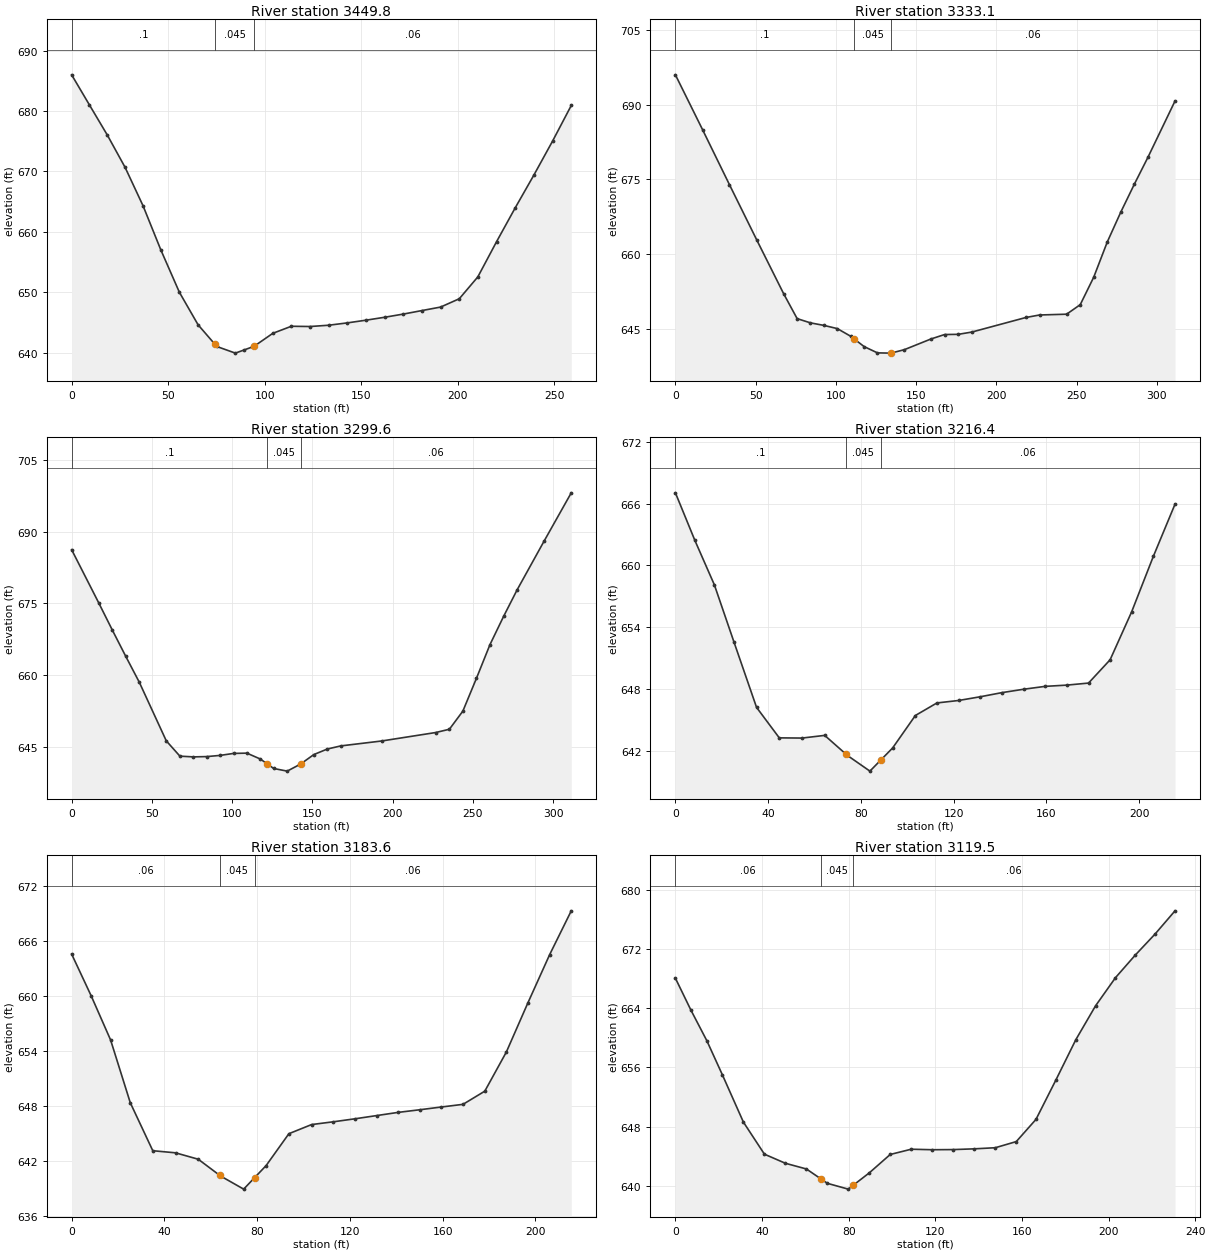
Type RM Length L Ch R = 1 ,3449.8  ,145.2,116.8,72
XS GIS Cut Line= 3
     1766374.182      479243.202     1766417.151      479226.275
     1766608.557      479133.827
#Sta/Elev= 30
       0  686.01     9.2  681.03    18.5  676.02    27.7  670.67      37   664.3
    46.2     657    55.8  649.99    65.5  644.59    74.2  641.37    75.2     641
    84.8   639.9    89.2  640.41    94.5  641.03   104.2  643.18   113.8  644.35
   123.5  644.31   133.1  644.52   142.8  644.91   152.5  645.36   162.1  645.84
   171.8  646.37   181.4  646.95   191.1  647.53   200.8  648.91   210.4  652.53
   220.1  658.36   229.8  663.99   239.4  669.38   249.1  675.02   258.8  680.93
#Mann= 3 , 0 , 0
       0      .1       0    74.2    .045       0    94.5     .06       0
Bank Sta=74.2,94.5
XS Rating Curve= 0 ,0
Exp/Cntr=0.3,0.1

Type RM Length L Ch R = 1 ,3333.1  ,39,33.5,50.7
XS GIS Cut Line= 4
     1766413.245      479381.223     1766499.182      479364.296
     1766496.578      479267.942     1766648.922      479180.702
#Sta/Elev= 29
       0  695.99  16.887  685.01  33.688  673.95  50.576  662.94  67.463  652.07
  75.864  647.08  84.178  646.23  92.578  645.72 100.892  645.08 109.206  643.55
 111.284  643.04 117.606  641.47  125.92  640.21 134.321  640.16 142.634  640.85
 159.349  643.01 167.749  643.89 176.236  643.93 184.637  644.38 218.412  647.31
 226.899  647.81 243.786  647.97 252.273  649.88 260.674  655.39 269.161  662.49
 277.561  668.46 286.048  674.09 294.449  679.44 311.336  690.74
#Mann= 3 , 0 , 0
       0      .1       0 111.284    .045       0 134.321     .06       0
Bank Sta=111.284,134.321
XS Rating Curve= 0 ,0
Skew Angle= 30
Exp/Cntr=0.3,0.1

Type RM Length L Ch R = 1 ,3299.6  ,42.5,83.2,117.1
XS GIS Cut Line= 4
     1766441.891      479411.171     1766527.828      479394.244
     1766525.224       479297.89     1766677.568       479210.65
#Sta/Elev= 30
       0  686.21  16.887  675.12  25.288   669.5  33.688     664  42.175  658.57
  58.976  646.36  67.463  643.17  75.864  643.02  84.178  643.08  92.578  643.33
 100.892  643.74 109.206   643.8 117.606  642.57  121.85  641.56  125.92   640.6
 134.321  640.05 142.634  641.52 150.948  643.51 159.349  644.66 167.749  645.31
 193.124  646.33 226.899   648.1 235.386  648.78 243.786  652.56 252.273  659.42
 260.674  666.42 269.161   672.3 277.561  677.82 294.449  688.03 311.336  698.07
#Mann= 3 , 0 , 0
       0      .1       0  121.85    .045       0 142.634     .06       0
Bank Sta=121.85,142.634
XS Rating Curve= 0 ,0
Skew Angle= 30
Exp/Cntr=0.3,0.1

Type RM Length L Ch R = 1 ,3216.4  ,32.8,32.8,32.8
XS GIS Cut Line= 4
     1766479.217      479421.588     1766503.522      479414.643
     1766580.779       479402.49     1766686.682      479366.032
#Sta/Elev= 26
       0  667.05     8.4  662.43    16.8  658.12    25.3  652.54      35  646.22
    44.8  643.26    54.6  643.24    64.4   643.5    73.6  641.67    74.2  641.55
    83.9  640.03    88.6  641.11    93.7  642.28   103.5  645.43   112.8  646.65
   122.2  646.89   131.5  647.25   140.8  647.65   150.2  647.98   159.5  648.26
   168.8  648.38   178.2  648.58   187.5  650.84   196.8   655.5   206.2  660.91
   215.5  665.95
#Mann= 3 , 0 , 0
       0      .1       0    73.6    .045       0    88.6     .06       0
Bank Sta=73.6,88.6
XS Rating Curve= 0 ,0
Exp/Cntr=0.3,0.1

Type RM Length L Ch R = 1 ,3183.6  ,61.9,64.1,66.3
XS GIS Cut Line= 4
     1766490.502      479452.838     1766514.807      479445.893
     1766592.064       479433.74     1766697.967      479397.282
#Sta/Elev= 26
       0  664.61     8.4  660.06    16.8  655.22    25.3  648.35      35  643.11
    44.8  642.88    54.6  642.18    63.9  640.41    64.4  640.32    74.2  638.91
    78.9  640.16    83.9  641.49    93.7  644.97   103.5  645.97   112.8  646.27
   122.2   646.6   131.5  646.95   140.8   647.3   150.2  647.59   159.5  647.89
   168.8  648.18   178.2  649.62   187.5   653.9   196.8  659.28   206.2  664.56
   215.5  669.34
#Mann= 3 , 0 , 0
       0     .06       0    63.9    .045       0    78.9     .06       0
Bank Sta=63.9,78.9
XS Rating Curve= 0 ,0
Exp/Cntr=0.3,0.1

Type RM Length L Ch R = 1 ,3119.5  ,115.1,116.6,118.1
XS GIS Cut Line= 4
     1766488.766      479506.657     1766510.467      479505.789
     1766645.884      479497.977       1766718.8      479505.789
#Sta/Elev= 28
       0  668.03     7.2   663.7    14.5   659.6    21.7  654.98    31.4   648.6
    41.1  644.27    50.8  643.04    60.5  642.27    67.1  640.95    70.2  640.33
    79.8  639.55    82.1  640.07    89.5  641.74    99.2  644.23   108.9  644.94
   118.6  644.87   128.3  644.89     138  644.99   147.7  645.14   157.4  645.97
   166.5  648.97   175.7  654.29   184.9  659.73     194   664.3   203.2   668.1
   212.4  671.17   221.5     674   230.7  677.13
#Mann= 3 , 0 , 0
       0     .06       0    67.1    .045       0    82.1     .06       0
Bank Sta=67.1,82.1
XS Rating Curve= 0 ,0
Exp/Cntr=0.3,0.1