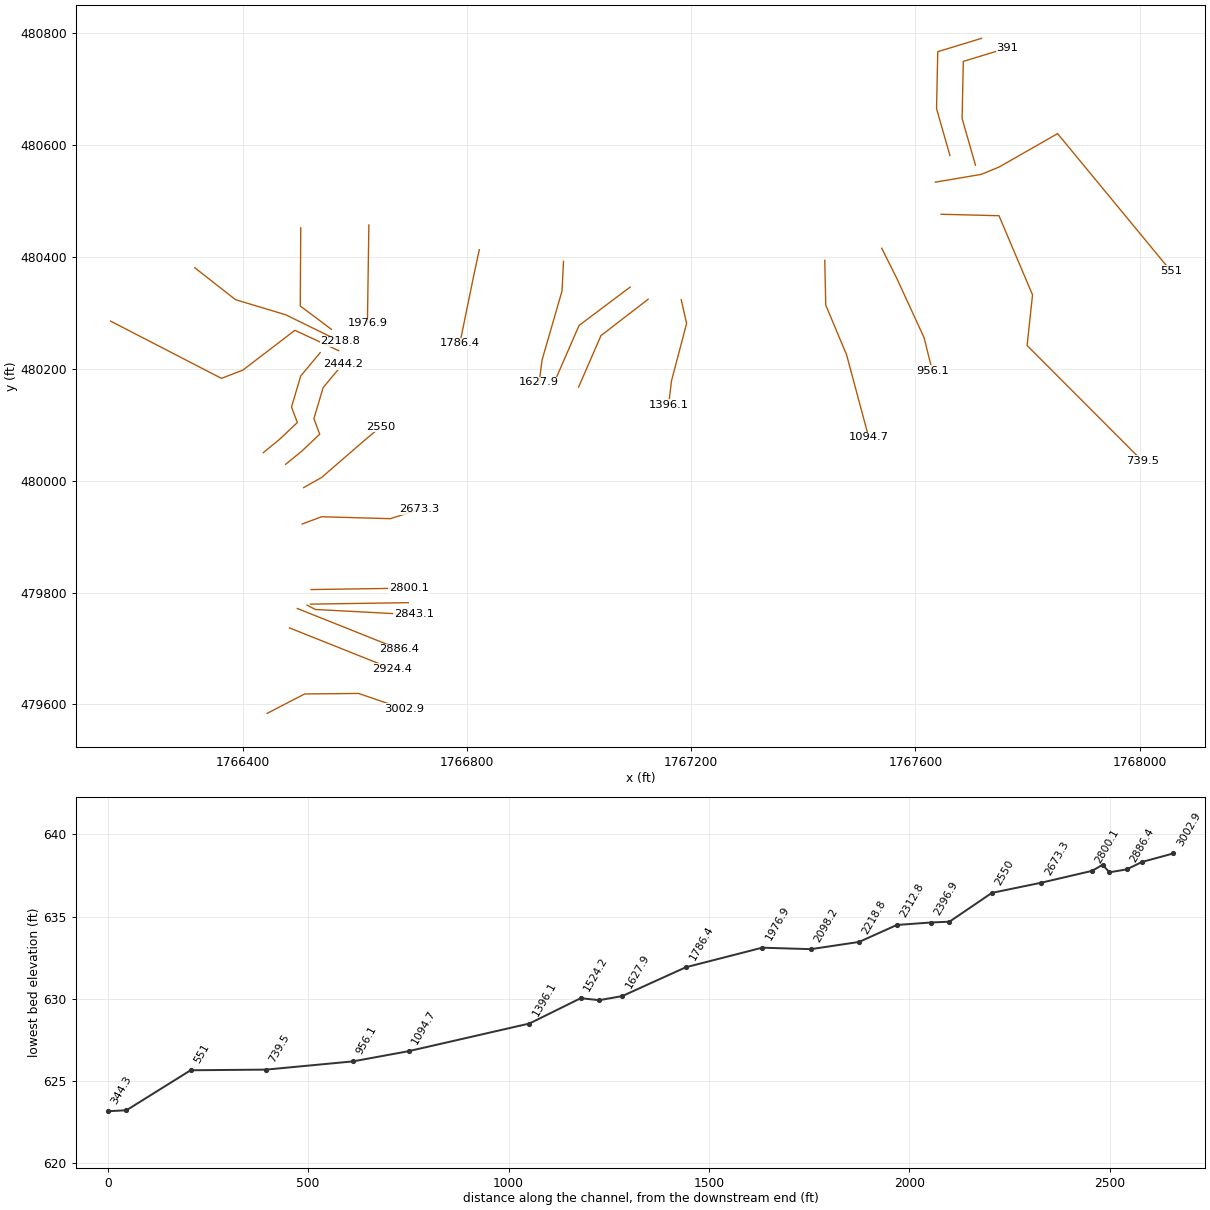
HEC-RAS study MIDFORK1.prj: MIDFORK1

--- MIDFORK1.g01 (geometry) --- (continued)

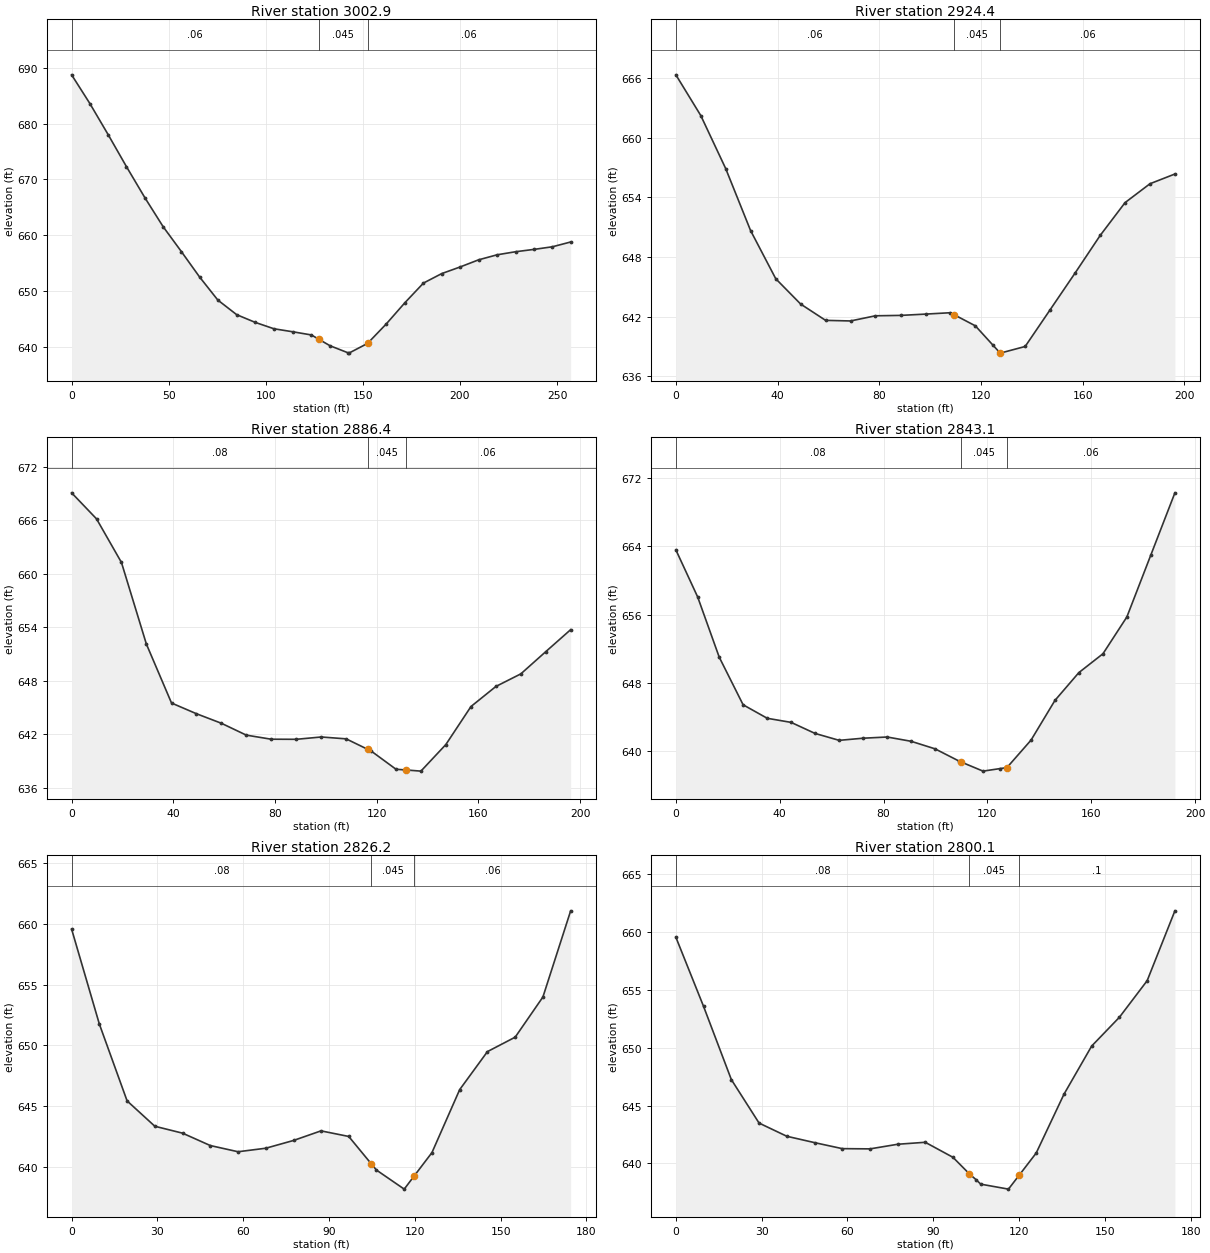
Type RM Length L Ch R = 1 ,3002.9  ,87.2,78.5,69.7
XS GIS Cut Line= 4
     1766443.627      479583.914     1766510.467      479618.636
     1766606.821      479619.504      1766687.55      479591.727
#Sta/Elev= 30
       0  688.77     9.4  683.62    18.8  678.05    28.2  672.32    37.7  666.74
    47.1  661.54    56.5  657.07    65.9   652.5    75.3  648.36      85  645.74
    94.6  644.35   104.2  643.21   113.9  642.67   123.5   642.1   127.2  641.35
   133.1  640.16   142.2  638.92   142.8  638.84   152.4  640.58     162  644.06
   171.7  647.91   181.2  651.41   190.6  653.11   200.1   654.3   209.6  655.58
   219.1  656.48   228.6  657.03   238.1  657.45   247.6  657.92     257  658.78
#Mann= 3 , 0 , 0
       0     .06       0   127.2    .045       0   152.4     .06       0
Bank Sta=127.2,152.4
XS Rating Curve= 0 ,0
Exp/Cntr=0.3,0.1

Type RM Length L Ch R = 1 ,2924.4  ,38,38,38
XS GIS Cut Line= 2
     1766483.557      479736.692     1766665.849      479663.775
#Sta/Elev= 23
       0  666.35     9.8  662.25    19.6  656.91    29.4  650.66    39.3  645.81
    49.1  643.26    58.9  641.62    68.7  641.56    78.5  642.08    88.4  642.12
    98.2  642.25     108  642.39   109.6  642.17   117.8  641.07   124.6  639.16
   127.6  638.32   137.4  638.99   147.2  642.68   157.1  646.41   166.9  650.17
   176.7  653.48   186.5  655.38   196.3  656.36
#Mann= 3 , 0 , 0
       0     .06       0   109.6    .045       0   127.6     .06       0
Bank Sta=109.6,127.6
XS Rating Curve= 0 ,0
Exp/Cntr=0.3,0.1

Type RM Length L Ch R = 1 ,2886.4  ,35.9,43.3,50.8
XS GIS Cut Line= 2
     1766497.446      479771.414     1766679.738      479698.497
#Sta/Elev= 23
       0  669.09     9.8  666.17    19.6  661.28    29.4  652.13    39.3  645.51
    49.1  644.31    58.9  643.24    68.7  641.91    78.5  641.45    88.4  641.44
    98.2   641.7     108  641.49   116.5  640.31   117.8  640.13   127.6  638.08
   131.5     638   137.4  637.87   147.2  640.85   157.1  645.12   166.9  647.37
   176.7  648.78   186.5  651.27   196.3  653.74
#Mann= 3 , 0 , 0
       0     .08       0   116.5    .045       0   131.5     .06       0
Bank Sta=116.5,131.5
XS Rating Curve= 0 ,0
Exp/Cntr=0.3,0.1

Type RM Length L Ch R = 1 ,2843.1  ,15.4,17,18.4
XS GIS Cut Line= 4
     1766514.807       479777.49     1766529.564      479769.678
     1766677.134      479761.865     1766704.911      479761.865
#Sta/Elev= 24
       0  663.57     8.4  658.06    16.7  651.02    25.9  645.45    35.2  643.87
    44.4  643.39    53.6   642.1    62.9  641.29    72.1  641.54    81.4  641.68
    90.6  641.18    99.8   640.3   109.1  638.86   109.7  638.78   118.3  637.69
   124.7  637.98   127.5   638.1   136.8  641.32     146  645.96   155.2  649.21
   164.5  651.42   173.7  655.72     183  663.02   192.2  670.24
#Mann= 3 , 0 , 0
       0     .08       0   109.7    .045       0   127.5     .06       0
Bank Sta=109.7,127.5
XS Rating Curve= 0 ,0
Exp/Cntr=0.3,0.1

Type RM Length L Ch R = 1 ,2826.2  ,26,26.1,26
XS GIS Cut Line= 2
     1766520.884      479779.227     1766695.363      479781.831
#Sta/Elev= 21
       0  659.57     9.7  651.75    19.4  645.42    29.1  643.33    38.8  642.76
    48.5  641.74    58.2  641.23    67.9  641.52    77.6  642.16    87.2  642.95
    96.9  642.49   104.8  640.23   106.6  639.72   116.3  638.15   119.8  639.24
     126  641.16   135.7  646.35   145.4  649.48   155.1  650.67   164.8  653.98
   174.5  661.08
#Mann= 3 , 0 , 0
       0     .08       0   104.8    .045       0   119.8     .06       0
Bank Sta=104.8,119.8
XS Rating Curve= 0 ,0
Exp/Cntr=0.3,0.1

Type RM Length L Ch R = 1 ,2800.1  ,127.8,126.8,125.8
XS GIS Cut Line= 2
     1766521.752      479805.268     1766696.231      479807.872
#Sta/Elev= 22
       0  659.56     9.7  653.57    19.4  647.25    29.1  643.49    38.8  642.35
    48.5   641.8    58.2  641.28    67.9  641.26    77.6  641.66    87.2  641.83
    96.9  640.53  102.67  639.09   105.1  638.57   106.6  638.21   116.3  637.78
   120.1     639     126   640.9   135.7  645.98   145.4  650.15   155.1  652.64
   164.8   655.8   174.5  661.84
#Mann= 3 , 0 , 0
       0     .08       0  102.67    .045       0   120.1      .1       0
Bank Sta=102.67,120.1
XS Rating Curve= 0 ,0
Exp/Cntr=0.3,0.1

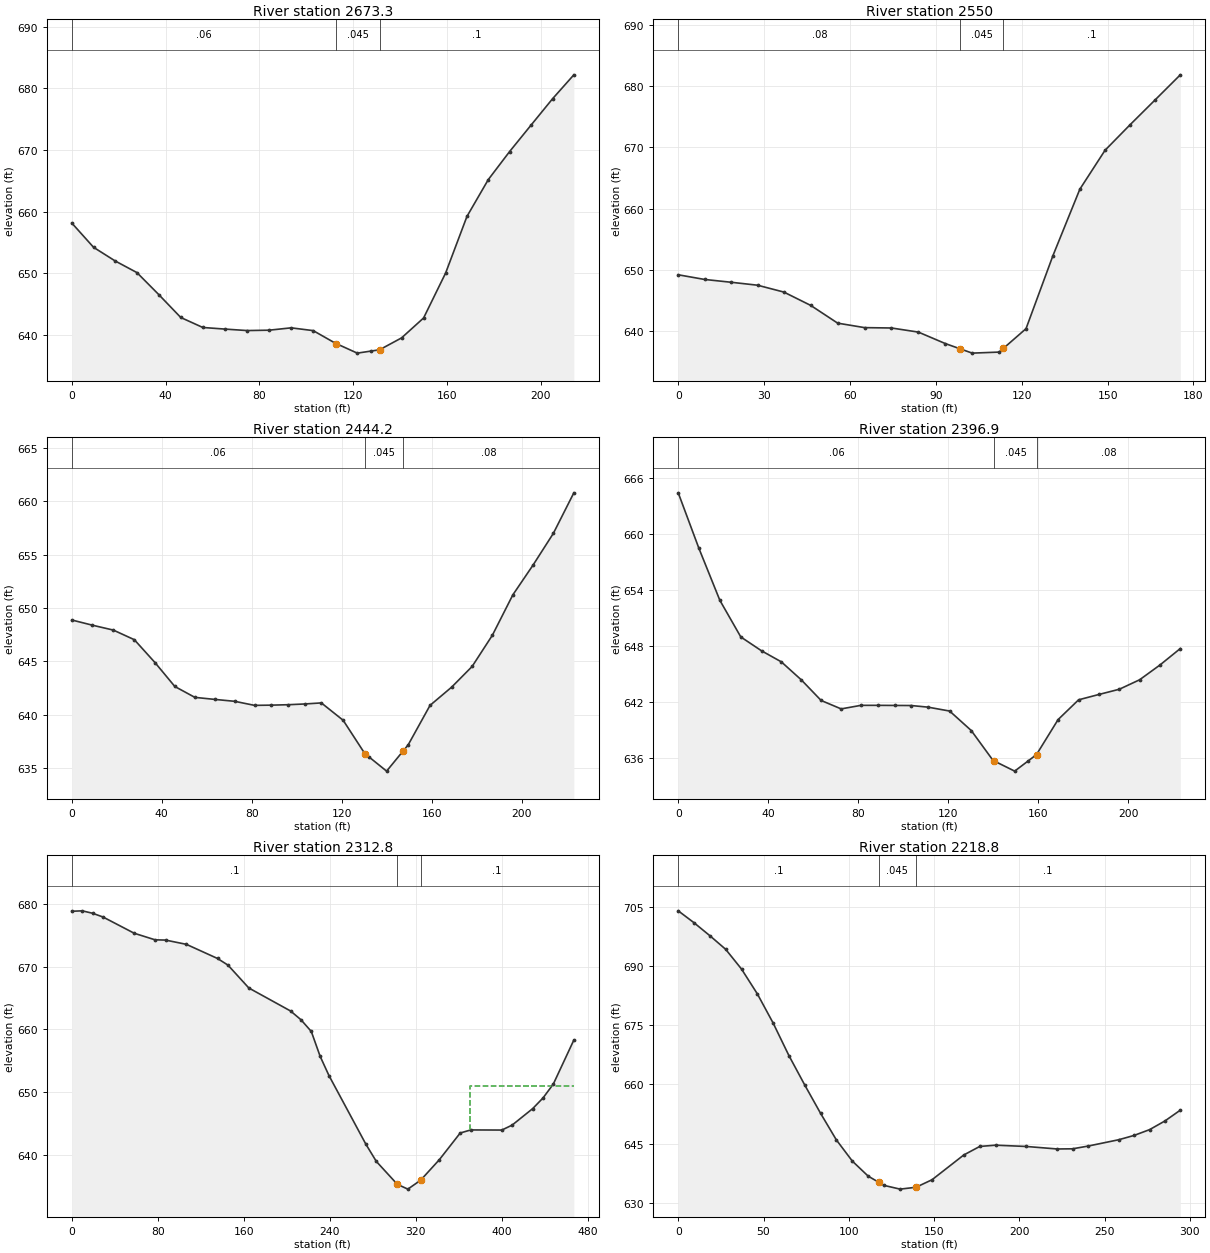
Type RM Length L Ch R = 1 ,2673.3  ,106.3,123.3,140.3
XS GIS Cut Line= 4
     1766506.127      479922.456     1766540.849      479935.477
     1766663.245      479932.004     1766715.328      479948.497
#Sta/Elev= 26
       0  658.16     9.3  654.22    18.5  652.01    27.8  650.12    37.1  646.56
    46.5  642.84    55.9  641.22    65.3  640.96    74.8  640.72    84.2  640.78
    93.6  641.16     103  640.71   112.4  638.68   112.8  638.61   121.8  637.06
   127.8   637.4   131.3   637.6   140.7  639.53   150.1  642.76   159.5  650.05
   168.6  659.23   177.7   665.2   186.8  669.75     196  674.06   205.1   678.3
   214.2  682.19
#Mann= 3 , 0 , 0
       0     .06       0   112.8    .045       0   131.3      .1       0
Bank Sta=112.8,131.3
XS Rating Curve= 0 ,0
Exp/Cntr=0.3,0.1

Type RM Length L Ch R = 1 ,2550    ,92.2,105.8,118.8
XS GIS Cut Line= 4
     1766508.731       479987.56     1766540.849      480005.789
     1766618.974      480073.497     1766645.884      480096.067
#Sta/Elev= 22
       0  649.22     9.2  648.46    18.5     648    27.7  647.52    36.9   646.4
    46.3  644.22    55.7  641.33    65.1   640.6    74.5  640.54    83.9  639.87
    93.3     638    98.6  637.12   102.7  636.44   112.1  636.61   113.6  637.22
   121.5  640.43   130.9  652.34   140.3  663.18   149.1  669.53   157.9  673.72
   166.6  677.75   175.4  681.84
#Mann= 3 , 0 , 0
       0     .08       0    98.6    .045       0   113.6      .1       0
Bank Sta=98.6,113.6
XS Rating Curve= 0 ,0
Exp/Cntr=0.3,0.1

Type RM Length L Ch R = 1 ,2444.2  ,47.8,47.3,46.1
XS GIS Cut Line= 6
     1766476.613      480029.227     1766505.259      480052.664
     1766537.377      480083.046      1766526.96      480110.824
     1766543.453      480166.379     1766578.175      480208.046
#Sta/Elev= 28
       0  648.87     9.2  648.38    18.5  647.92    27.8  647.02      37  644.87
    45.8  642.63    54.7  641.61    63.5  641.42    72.4  641.24    81.2  640.86
    88.6  640.88    96.1  640.92   103.5  640.99   110.9  641.09   120.6  639.46
   130.2  636.34   132.2     636   139.9  634.69   147.2  636.57   149.5  637.16
   159.2  640.86   168.8  642.57   177.9  644.51   186.9  647.44     196  651.23
     205  654.03     214     657   223.1   660.8
#Mann= 3 , 0 , 0
       0     .06       0   130.2    .045       0   147.2     .08       0
Bank Sta=130.2,147.2
XS Rating Curve= 0 ,0
Exp/Cntr=0.3,0.1

Type RM Length L Ch R = 1 ,2396.9  ,98.6,84.1,70.8
XS GIS Cut Line= 6
     1766436.682       480050.06     1766465.328      480073.497
     1766497.446      480103.879     1766487.029      480131.657
     1766503.522      480187.213     1766538.245      480228.879
#Sta/Elev= 28
       0  664.38     9.2  658.44    18.5  652.89    27.8  648.98      37   647.5
    45.8  646.32    54.7  644.39    63.5  642.19    72.4  641.29    81.2  641.67
    88.6  641.67    96.1  641.66   103.5  641.65   110.9  641.48   120.6  641.06
   130.2  638.98   139.9  635.78   140.5  635.71   149.5  634.64   155.5  635.73
   159.2  636.41   168.8  640.15   177.9  642.26   186.9  642.83     196  643.39
     205   644.4     214  645.97   223.1  647.74
#Mann= 3 , 0 , 0
       0     .06       0   140.5    .045       0   159.2     .08       0
Bank Sta=140.5,159.2
XS Rating Curve= 0 ,0
Exp/Cntr=0.3,0.1

Type RM Length L Ch R = 1 ,2312.8  ,115.5,94,72.4
XS GIS Cut Line= 5
     1766164.113      480285.303     1766362.029      480182.872
     1766400.224      480197.629     1766493.106       480268.81
     1766571.231      480232.352
#Sta/Elev= 30
       0  678.85     9.7  678.92    19.4  678.53    29.1  677.93    58.1  675.34
    77.5  674.29    87.2  674.25   106.6  673.57   135.6  671.31   145.3  670.25
   164.7   666.6   203.5  662.93   213.2  661.53   222.8  659.66     231   655.7
   239.2  652.63   273.6  641.65   283.3  638.91   302.8  635.26   312.6  634.49
   324.4   635.9   341.8  639.17   361.3  643.45   371.1  643.94     400  643.92
   409.6  644.71   428.7  647.34   438.3  649.04   447.9  651.26     467  658.29
#Mann= 3 , 0 , 0
       0      .1       0   302.8    .045       0   324.4      .1       0
#XS Ineff= 2 , 0
                          370.24          650.92
Permanent Ineff=
       F       F
Bank Sta=302.8,324.4
XS Rating Curve= 0 ,0
Exp/Cntr=0.3,0.1

Type RM Length L Ch R = 1 ,2218.8  ,150.4,120.6,90.6
XS GIS Cut Line= 4
     1766314.286      480380.789     1766387.203      480323.497
     1766476.613      480296.588     1766573.835      480248.845
#Sta/Elev= 30
       0  703.94     9.3  700.91    18.6  697.62    27.8   694.2    37.1   689.2
    46.4   682.9    55.6  675.56    64.9  667.28    74.2  659.81    83.5  652.63
    92.7  645.94   102.1  640.55   111.4  636.74   117.5  635.21   120.7   634.4
   130.1  633.46   139.4  633.93   148.8  635.83   167.4   642.1   176.8  644.27
   186.1  644.59   204.2  644.26   222.2  643.63   231.2  643.67   240.3  644.36
   258.3  645.97   267.3  647.06   276.4  648.53   285.4  650.73   294.4  653.46
#Mann= 3 , 0 , 0
       0      .1       0   117.5    .045       0   139.4      .1       0
Bank Sta=117.5,139.4
XS Rating Curve= 0 ,0
Exp/Cntr=0.3,0.1

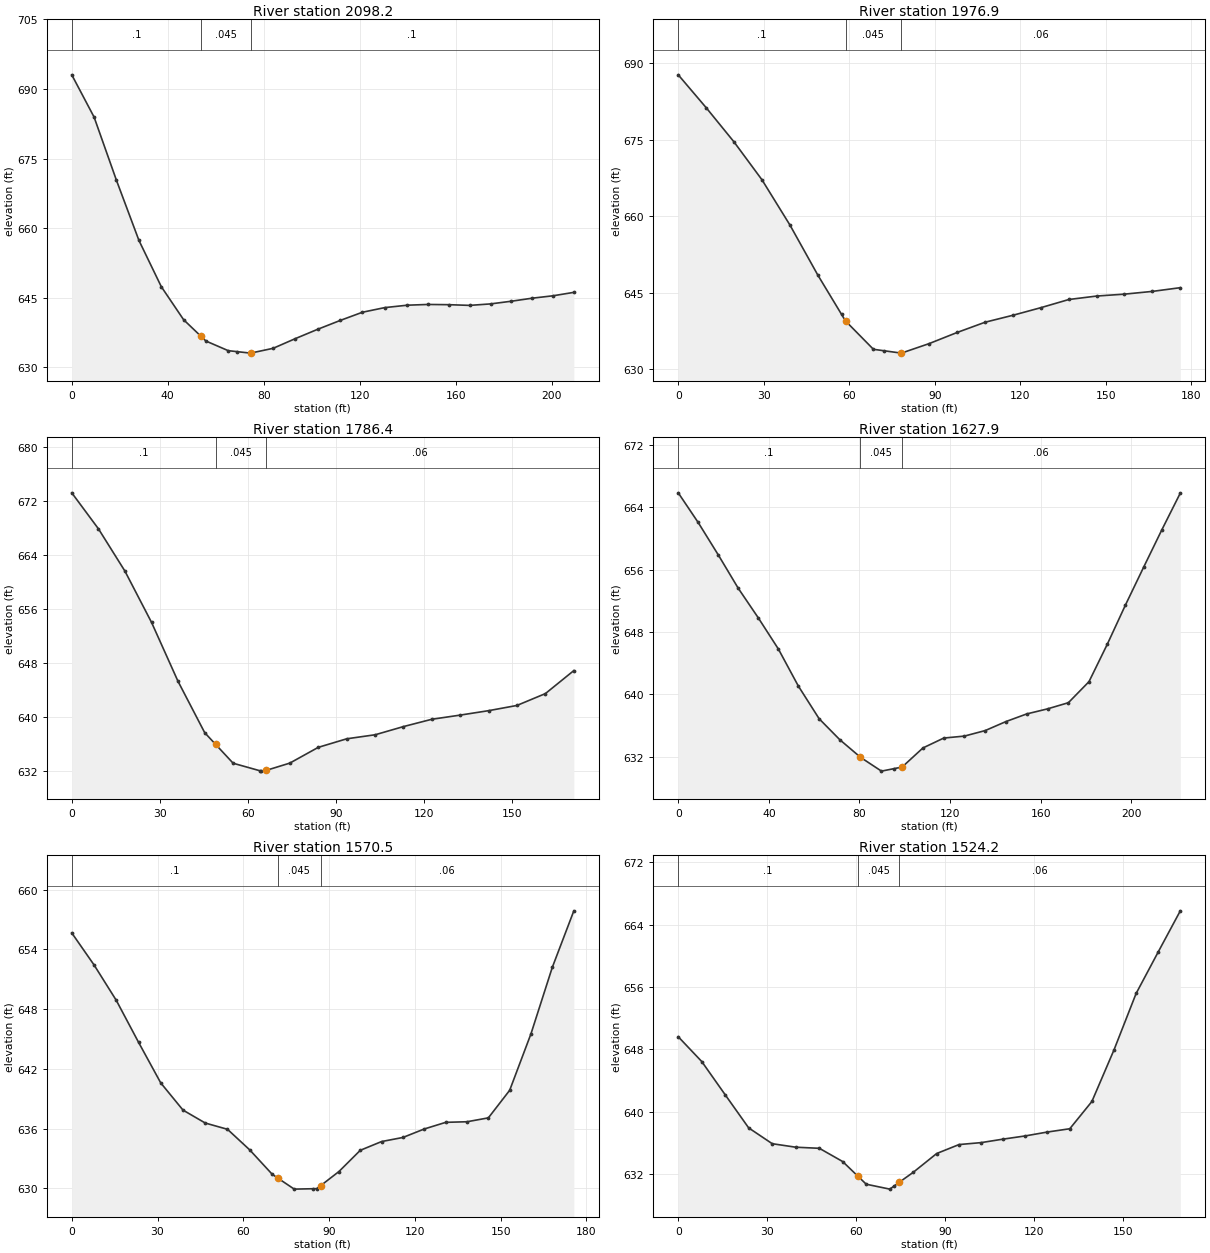
Type RM Length L Ch R = 1 ,2098.2  ,121.4,121.3,121.3
XS GIS Cut Line= 3
     1766503.522       480451.97     1766502.654      480312.213
      1766558.21      480270.546
#Sta/Elev= 26
       0  693.06     9.3  683.94    18.6  670.33      28  657.32    37.3  647.36
    46.6  640.23    53.9  636.62    55.9  635.63    65.2  633.55    68.9  633.34
    74.5  633.02    83.9  634.06    93.2  636.16   102.5  638.17   111.8  640.06
   121.1  641.84   130.4  642.84   139.8  643.36   148.4  643.52   157.1  643.47
   165.8  643.32   174.5  643.64   183.2  644.22   191.8  644.87   200.5  645.39
   209.2  646.13
#Mann= 3 , 0 , 0
       0      .1       0    53.9    .045       0    74.5      .1       0
Bank Sta=53.9,74.5
XS Rating Curve= 0 ,0
Exp/Cntr=0.3,0.1

Type RM Length L Ch R = 1 ,1976.9  ,194.8,190.5,186.2
XS GIS Cut Line= 2
      1766625.05      480457.178     1766622.446      480280.963
#Sta/Elev= 21
       0  687.75     9.8   681.3    19.6  674.56    29.4  667.13    39.2  658.26
      49  648.42    57.3  640.73    58.7  639.43    68.5  633.86    72.3  633.57
    78.3  633.11    88.1  634.99    97.9  637.17   107.7  639.18   117.5  640.55
   127.3  642.04   137.1  643.64   146.9  644.32   156.6  644.69   166.4  645.23
   176.2  645.96
#Mann= 3 , 0 , 0
       0      .1       0    58.7    .045       0    78.3     .06       0
Bank Sta=58.7,78.3
XS Rating Curve= 0 ,0
Exp/Cntr=0.3,0.1

Type RM Length L Ch R = 1 ,1786.4  ,160.1,158.5,156.7
XS GIS Cut Line= 3
     1766822.099      480412.907      1766812.55      480368.636
     1766787.377      480245.372
#Sta/Elev= 22
       0  673.24     9.1  667.89    18.1  661.63    27.2  653.99    36.2  645.26
  45.301  637.63  48.999   635.9      55  633.09      64  631.99    64.6  631.92
   66.32  632.04    74.3  633.11      84  635.45  93.701  636.72   103.4  637.32
     113  638.53   122.7  639.62   132.4  640.24 142.101   640.9   151.7  641.67
   161.4  643.43   171.1  646.85
#Mann= 3 , 0 , 0
       0      .1       0  48.999    .045       0   66.32     .06       0
Bank Sta=48.999,66.32
XS Rating Curve= 0 ,0
Exp/Cntr=0.3,0.1

Type RM Length L Ch R = 1 ,1627.9  ,74.1,57.4,45.3
XS GIS Cut Line= 4
     1766972.272      480392.074     1766969.668      480339.122
     1766934.078      480215.858      1766928.87      480175.928
#Sta/Elev= 28
       0  665.84     8.8  662.04    17.7  657.87    26.5   653.6    35.3  649.83
    44.2  645.82      53  641.08    62.2  636.88    71.3   634.2    80.1  632.03
    80.5  631.93    89.7  630.17    95.1  630.48    98.8  630.69     108  633.14
   117.2  634.41   126.3  634.66   135.5  635.37   144.7  636.53   153.8   637.5
     163  638.15   172.2  638.94   181.3  641.64   189.4  646.45   197.4  651.47
   205.5  656.36   213.5  661.13   221.6  665.81
#Mann= 3 , 0 , 0
       0      .1       0    80.1    .045       0    98.8     .06       0
Bank Sta=80.1,98.8
XS Rating Curve= 0 ,0
Exp/Cntr=0.3,0.1

Type RM Length L Ch R = 1 ,1570.5  ,45.9,46.3,43.3
XS GIS Cut Line= 3
     1767091.196      480346.067      1767000.05       480277.49
      1766960.12      480185.477
#Sta/Elev= 27
       0  655.66   7.782  652.45  15.564  648.89  23.346  644.68  31.128  640.59
   38.91  637.86  46.692  636.56  54.474  635.93  62.256  633.86  70.119  631.41
  72.167  631.01  77.819  629.92  84.455  629.96  85.683  629.97  87.068  630.27
  93.465  631.69  100.92  633.82 108.374   634.7 115.828  635.11 123.282  635.96
 130.819  636.63 138.273  636.69 145.727  637.08 153.181  639.85 160.636  645.53
  168.09   652.2 175.626  657.88
#Mann= 3 , 0 , 0
       0      .1       0  72.167    .045       0  87.068     .06       0
Bank Sta=72.167,87.068
XS Rating Curve= 0 ,0
Skew Angle= 35
Exp/Cntr=0.3,0.1

Type RM Length L Ch R = 1 ,1524.2  ,111.1,128.1,143.5
XS GIS Cut Line= 3
     1767123.314      480324.365     1767039.113      480259.261
     1766999.182      480167.247
#Sta/Elev= 26
       0   649.6   7.946  646.41  15.892  642.12  23.755   637.9  31.701  635.87
  39.647  635.42  47.593  635.28  55.457  633.58  60.535  631.72  63.402  630.67
  71.348  630.04  72.823  630.44  74.551  630.92  79.294  632.21  87.158  634.61
  94.694  635.76 102.148  636.01 109.603  636.46 117.057  636.87 124.511  637.37
 132.047  637.79 139.502  641.29 146.956  647.91  154.41  655.15 161.864  660.48
 169.319  665.76
#Mann= 3 , 0 , 0
       0      .1       0  60.535    .045       0  74.551     .06       0
Bank Sta=60.535,74.551
XS Rating Curve= 0 ,0
Skew Angle= 35
Exp/Cntr=0.3,0.1

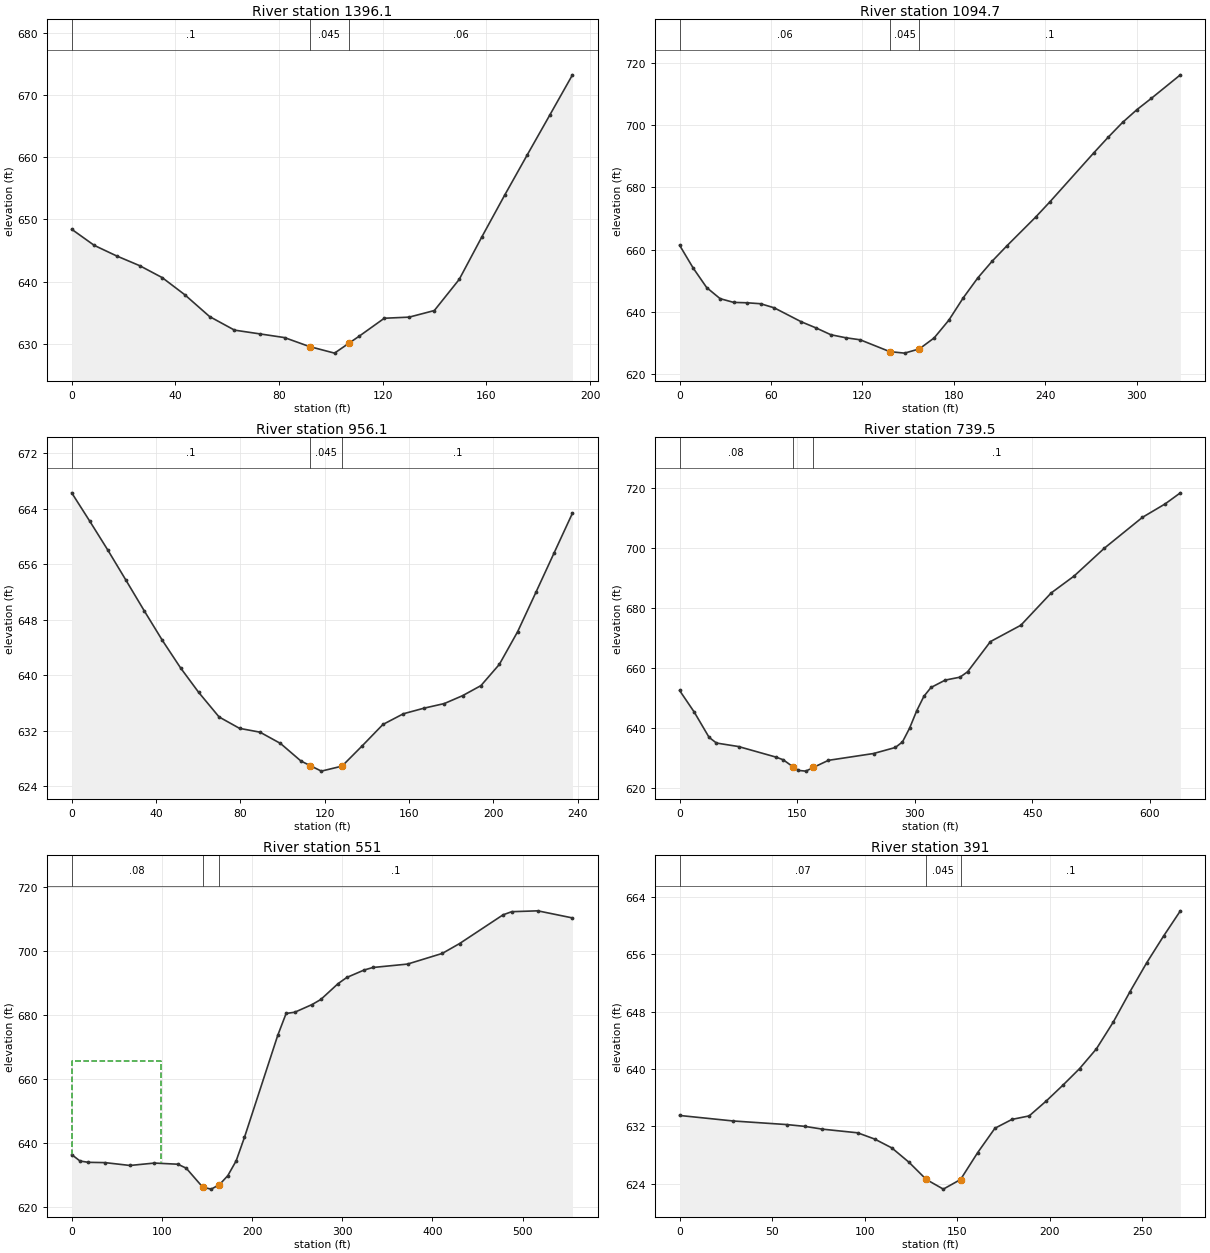
Type RM Length L Ch R = 1 ,1396.1  ,286.5,301.4,316
XS GIS Cut Line= 4
     1767182.342      480323.497     1767191.891      480280.963
     1767164.981      480178.532     1767159.772      480135.129
#Sta/Elev= 24
       0  648.42     8.7  645.83    17.4  644.12    26.2  642.57    34.9  640.65
    43.6   637.9    53.2  634.38    62.8   632.2    72.5   631.6    82.1     631
    91.7  629.56    91.8  629.55   101.4   628.5   106.8  630.05     111  631.25
   120.6  634.11   130.2  634.29   139.9  635.35   149.5  640.36   158.2  647.17
     167  653.88   175.7  660.35   184.5  666.83   193.2  673.26
#Mann= 3 , 0 , 0
       0      .1       0    91.8    .045       0   106.8     .06       0
Bank Sta=91.8,106.8
XS Rating Curve= 0 ,0
Exp/Cntr=0.3,0.1

Type RM Length L Ch R = 1 ,1094.7  ,138.1,138.7,139.4
XS GIS Cut Line= 4
     1767438.418       480393.81     1767440.154      480313.949
     1767477.481      480224.539      1767516.76      480077.621
#Sta/Elev= 30
       0  661.41     8.9  654.12    17.8  647.83    26.6  644.29    35.5  643.09
    44.4  642.96    53.2  642.66    62.1  641.35    79.9  636.87    89.6   634.9
    99.3  632.72     109  631.76   118.6  631.09     138   627.3   147.7  626.82
   157.4  628.17   167.1  631.68   176.8   637.4   186.3  644.59   195.8  650.95
   205.3  656.35   214.8  661.18   233.8  670.45   243.3  675.42   271.8  690.96
   281.3     696   290.8  700.78   300.3  704.91   309.8  708.54   328.8  716.06
#Mann= 3 , 0 , 0
       0     .06       0     138    .045       0   157.4      .1       0
Bank Sta=138,157.4
XS Rating Curve= 0 ,0
Exp/Cntr=0.3,0.1

Type RM Length L Ch R = 1 ,956.1   ,217.1,216.6,216
XS GIS Cut Line= 4
     1767539.981      480415.511     1767566.891      480361.692
     1767615.502      480255.789     1767630.259      480196.761
#Sta/Elev= 28
       0  666.28     8.6  662.18    17.2     658    25.8  653.66    34.4  649.29
      43  645.03    51.6  641.08    60.2  637.55    69.9     634    79.6  632.36
    89.3  631.81      99  630.19   108.7  627.66   113.2  626.98   118.4   626.2
   128.2  626.92   137.9  629.88   147.6  632.92   157.3  634.46     167  635.26
   176.7  635.93   185.4  637.07   194.1  638.52   202.8  641.57   211.5  646.29
   220.2  651.98   228.8  657.64   237.5  663.36
#Mann= 3 , 0 , 0
       0      .1       0   113.2    .045       0   128.2      .1       0
Bank Sta=113.2,128.2
XS Rating Curve= 0 ,0
Exp/Cntr=0.3,0.1

Type RM Length L Ch R = 1 ,739.5   ,149.3,188.5,226.4
XS GIS Cut Line= 5
     1767645.884      480476.275     1767749.182      480473.671
     1767809.078      480332.178     1767799.379      480241.653
     1768004.586      480035.592
#Sta/Elev= 30
       0  652.54    18.8   645.3    37.6  636.95      47  635.05    75.2  633.88
   122.5   630.4   132.1  629.49   144.5  627.17   151.4  625.94     161   625.7
   170.6  626.92   189.8  629.29   247.4  631.56   275.2  633.57   284.3  635.42
   293.4  640.01   302.5   645.8   311.6  650.59   320.7  653.54   338.9     656
   357.7  656.97   367.4  658.77   396.5  668.81   435.3  674.25     474     685
   503.1   690.6   541.9  699.91   590.4  710.16   619.4  714.64   638.8  718.32
#Mann= 3 , 0 , 0
       0     .08       0   144.5    .045       0   170.6      .1       0
Bank Sta=144.5,170.6
XS Rating Curve= 0 ,0
Exp/Cntr=0.3,0.1

Type RM Length L Ch R = 1 ,551     ,133.1,160,183.8
XS GIS Cut Line= 5
     1767635.662      480533.639     1767717.559      480547.575
     1767749.595      480560.766     1767853.761      480620.445
     1768055.584      480375.219
#Sta/Elev= 30
       0  636.45     9.2  634.44    18.5  634.03    36.9  633.94    64.6  633.05
    91.7   633.8   117.7  633.44     127  632.21   145.4  626.24   154.7  625.66
   163.9  627.07   173.1  629.86   182.4   634.5   191.6  641.84   228.5  673.68
   237.8  680.53   247.4  680.91   266.6  683.31   276.3   684.9   295.5  689.86
   305.1  691.77   324.4   694.1     334  694.88   372.5  695.95     411  699.28
   430.2  702.36   478.4  711.33     488  712.31   516.9  712.58   555.4  710.36
#Mann= 3 , 0 , 0
       0     .08       0   145.4    .045       0   163.9      .1       0
#XS Ineff= 2 , 0
           98.56  665.55
Permanent Ineff=
       F       F
Bank Sta=145.4,163.9
XS Rating Curve= 0 ,0
Exp/Cntr=0.3,0.1

Type RM Length L Ch R = 1 ,391     ,50.2,46.7,46.5
XS GIS Cut Line= 4
     1767707.277      480564.021     1767683.405      480647.571
     1767685.575      480749.568       1767763.7       480773.44
#Sta/Elev= 25
       0  633.51      29  632.74    57.9  632.24    67.6  631.99    77.2   631.6
    96.2  631.09   105.4  630.22   114.7  628.98     124  626.97   133.3  624.58
   142.5  623.23   151.8  624.57   161.1  628.34   170.4  631.73   179.6  632.96
   188.9  633.45     198   635.5   207.1  637.73   216.1  640.04   225.2   642.8
   234.3  646.53   243.4   650.8   252.4  654.82   261.5  658.54   270.6  662.07
#Mann= 3 , 0 , 0
       0     .07       0   133.3    .045       0   151.8      .1       0
Bank Sta=133.3,151.8
XS Rating Curve= 0 ,0
Exp/Cntr=0.3,0.1

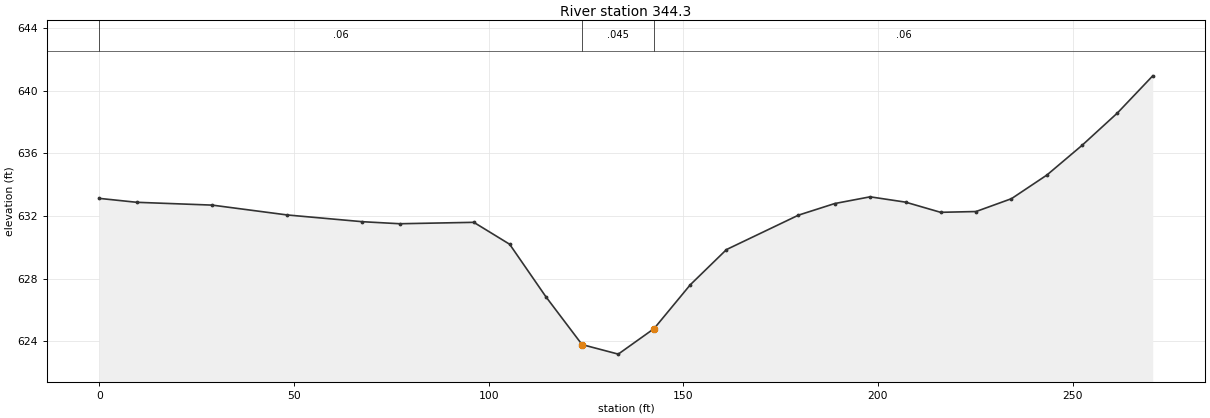
Type RM Length L Ch R = 1 ,344.3   ,43,38.6,33.9
XS GIS Cut Line= 4
     1767661.704      480581.382     1767637.832      480664.933
     1767640.003      480766.929     1767718.128      480790.801
#Sta/Elev= 25
       0  633.12     9.6  632.87      29  632.69    48.3  632.06    67.6  631.63
    77.2   631.5    96.2  631.59   105.4  630.19   114.7  626.84     124  623.78
   133.3  623.17   142.5   624.8   151.8   627.6   161.1  629.85   179.6  632.05
   188.9  632.79     198  633.22   207.1  632.88   216.1  632.23   225.2  632.28
   234.3   633.1   243.4  634.61   252.4   636.5   261.5  638.57   270.6  640.95
#Mann= 3 , 0 , 0
       0     .06       0     124    .045       0   142.5     .06       0
Bank Sta=124,142.5
XS Rating Curve= 0 ,0
Exp/Cntr=0.3,0.1