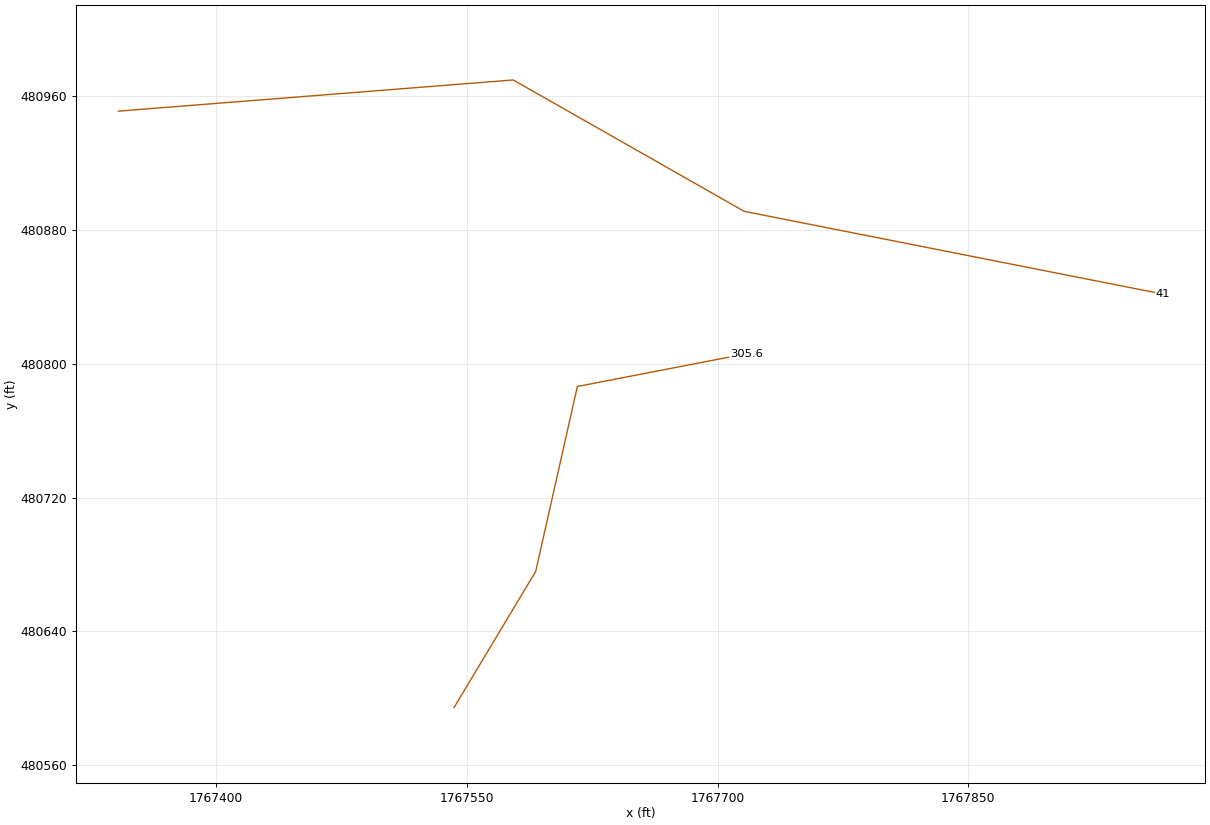
HEC-RAS study MIDFORK1.prj: MIDFORK1

--- MIDFORK1.g01 (geometry) --- (continued)

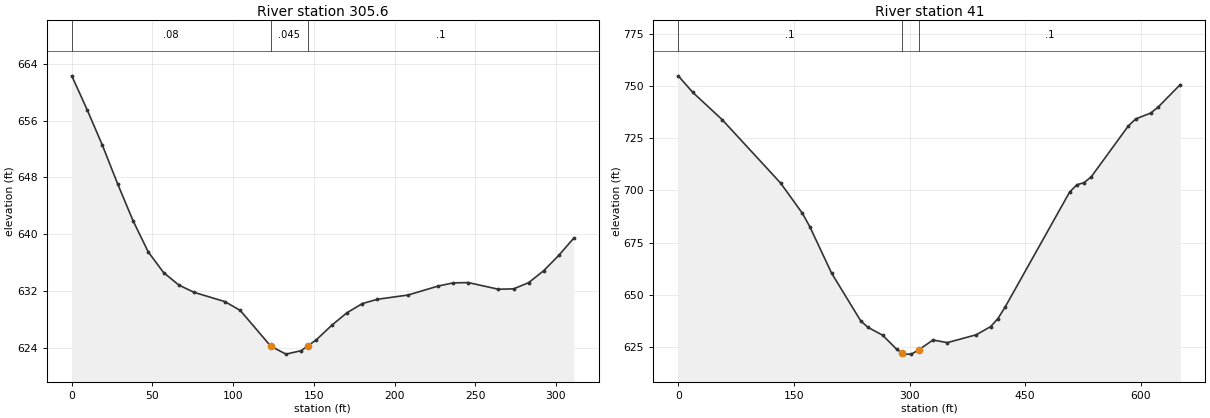
Type RM Length L Ch R = 1 ,305.6   ,307.8,264.6,221.4
XS GIS Cut Line= 4
     1767542.346      480594.403     1767591.174      480675.783
     1767616.131       480786.46     1767717.042      480805.992
#Sta/Elev= 30
       0  662.31     9.5  657.55      19  652.53    28.5  647.06      38   641.9
    47.4  637.52    56.9  634.62    66.4  632.85    75.9  631.83    94.9  630.53
   104.4  629.29   123.3  624.26   132.7  623.14   142.2  623.63   146.4  624.32
   151.6  625.17   161.1   627.2   170.5  628.96     180  630.25   189.4  630.86
   208.4  631.46     227  632.72   236.4  633.17   245.7  633.21   264.4  632.27
   273.8  632.33   283.1   633.2   292.5   634.9   301.8  637.05   311.1  639.48
#Mann= 3 , 0 , 0
       0     .08       0   123.3    .045       0   146.4      .1       0
Bank Sta=123.3,146.4
XS Rating Curve= 0 ,0
Exp/Cntr=0.3,0.1

Type RM Length L Ch R = 1 ,41      ,40.7,41,41.4
XS GIS Cut Line= 5
     1767341.592      480951.153     1767577.747      480969.799
     1767715.944      480891.204     1767853.122        480864.1
     1767966.376      480841.721
#Sta/Elev= 30
       0  754.76      19   746.8    56.8  733.86   132.7   703.5   161.1  688.98
   170.6  682.63     199  660.32   236.9  637.43   246.2  634.44     265  630.71
   283.6  623.88   290.3  622.28     293  621.64   302.4  621.64   311.7  623.62
   330.4  628.39   349.1  627.15   386.5   630.9   405.2  634.81   414.5  638.58
   423.8  644.04   507.7   699.2   517.1  702.66   526.4  703.68   535.7  706.46
   583.8   730.8   593.4  734.16   612.7  736.94   622.3  739.74   651.2  750.61
#Mann= 3 , 0 , 0
       0      .1       0   290.3    .045       0   311.7      .1       0
Bank Sta=290.3,311.7
XS Rating Curve= 0 ,0
Exp/Cntr=0.3,0.1

Chan Stop Cuts=-1
Use User Specified Reach Order=0
Composite Channel Slope=5